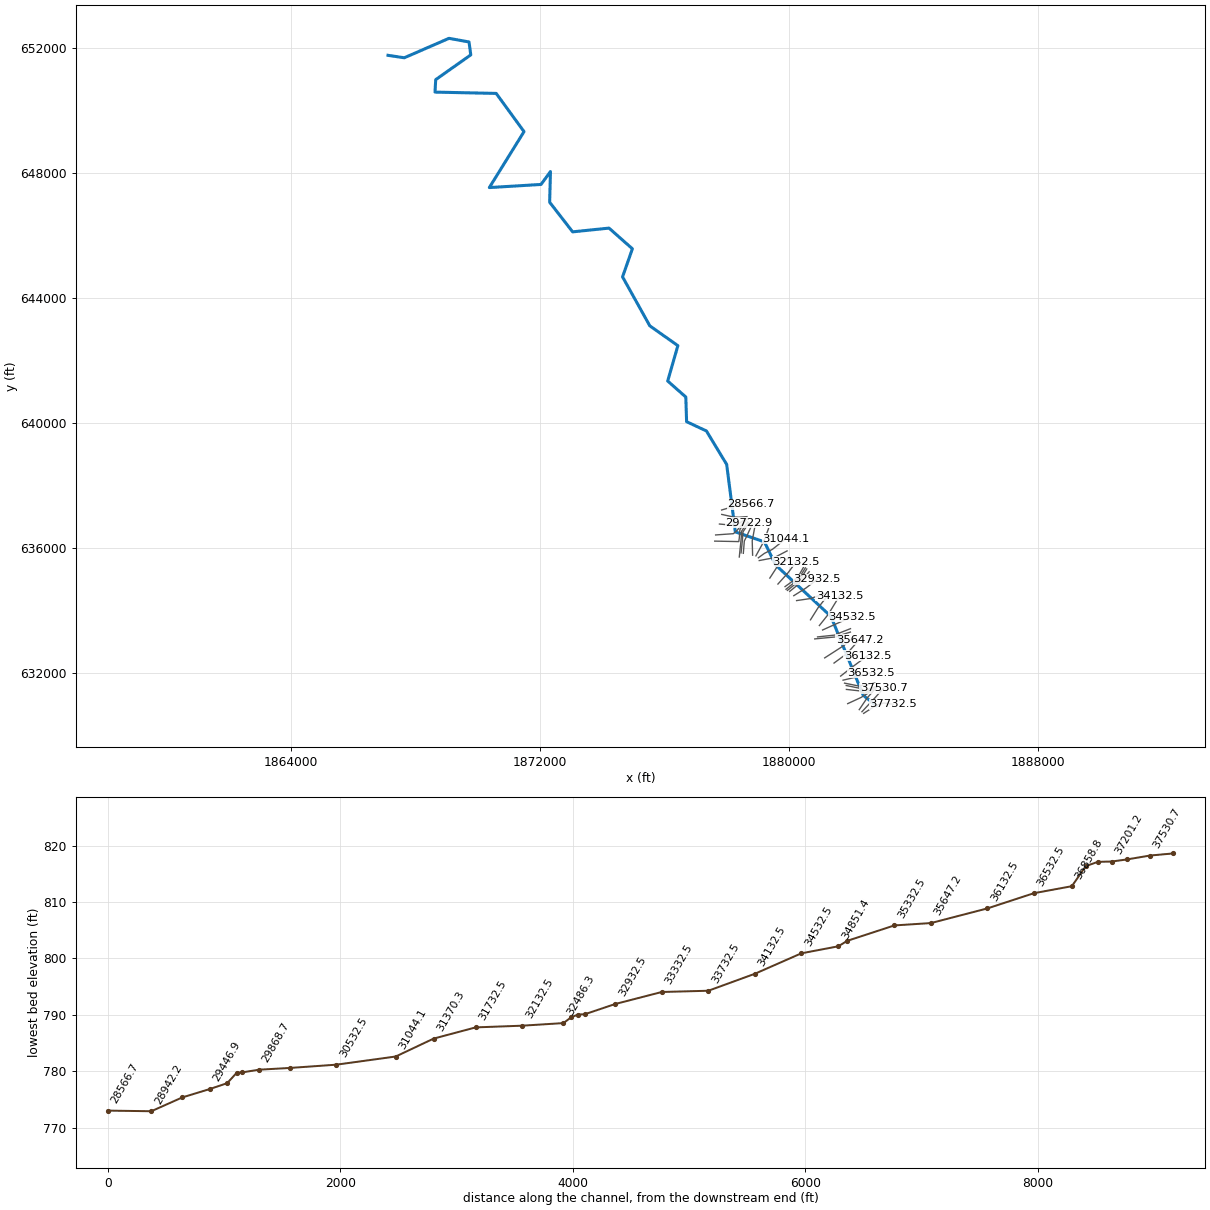
--- LFSpringCk.prj (project) ---

Proj Title=LFSpringCk
Current Plan=p01
Default Exp/Contr=0,0
English Units
Geom File=g01
Flow File=f01
Plan File=p01
BEGIN DESCRIPTION:
AMEC Environment & Infrastructure, 2013
Projection: NAD 1983 State Plane West Virginia South FIPS 4702 (US Feet)
Vertical Datum: NAVD 1988
END DESCRIPTION:
DSS Export Rating Curves= 0
DSS Export Rating Curve Sorted= 0
DSS Export Volume Flow Curves= 0
DXF OffsetX= 0
DXF OffsetY= 0
DXF ScaleX= 0
DXF ScaleY= 0

--- LFSpringCk.p01 (plan) ---

Plan Title=Floodplain
Program Version=4.00
Geom File=g01
Flow File=f01
K Sum by GR=0
Std Step Tol=0.01
Critical Tol=0.01
Num of Std Step Trials=20
Max Error Tol=0.3
Flow Tol Ratio=0.001
Split Flow NTrial=30
Split Flow Tol=0.02
Split Flow Ratio=0.02
Log Output Level=0
Friction Slope Method=1
Unsteady Friction Slope Method=2
Unsteady Bridges Friction Slope Method=1
Global Log Level=0
CheckData=False
Run HTab=0
Run UNet=0
Run PostProcess=0
UNET Theta=0
UNET Theta Warmup=0
UNET ZTol=0
UNET ZSATol=0
UNET MxIter=0
UNET MaxInSteps=0
UNET DtIC=0
UNET DtMin=0
UNET MaxCRTS=0
UNET WFStab=0
UNET SFStab=0
UNET WFX=0
UNET SFX=0
UNET DSS MLevel=0
UNET DZMax Abort=0
UNET Convert EG Bridges=0
UNET Use Existing IB Tables=0
UNET Froude Limit=0
UNET Froude Power=0
Write IC File=0
Echo Input=False
Echo Output=False
Write Detailed=0

--- LFSpringCk.f01 (steady flow) ---

Flow Title=NFF Regression Equation
Program Version=4.10
Number of Profiles= 1
Profile Names=P100yr
River Rch & RM=LFSpringCk,Main            ,37732.5
947.6503
River Rch & RM=LFSpringCk,Main            ,36858.8
976.4719
River Rch & RM=LFSpringCk,Main            ,35647.2
1068.822
River Rch & RM=LFSpringCk,Main            ,34532.5
 1149.54
River Rch & RM=LFSpringCk,Main            ,33332.5
1207.026
River Rch & RM=LFSpringCk,Main            ,29868.7
1340.407
River Rch & RM=LFSpringCk,Main            ,29722.9
1625.726
River Rch & RM=LFSpringCk,Main            ,26532.5
1689.966
River Rch & RM=LFSpringCk,Main            ,21482.7
1873.951
River Rch & RM=LFSpringCk,Main            ,21087.5
2890.813
River Rch & RM=LFSpringCk,Main            ,11756.4
3175.313
River Rch & RM=LFSpringCk,Main            ,11178.2
3838.524
River Rch & RM=LFSpringCk,Main            ,640.4
4009.373
River Rch & RM=LFSpringCk,Main            ,140.6
4010.818
Boundary for River Rch & Prof#=LFSpringCk,Main            , 1
Up Type= 0
Dn Type= 3
Dn Slope=0.00056
DSS Import GetInterval= 0
DSS Import GetPeak= 0
DSS Import FillOption= 0

--- LFSpringCk.g01 (geometry) ---

Geom Title=USGS 3m DEM
Program Version=4.10

River Reach=LFSpringCk      ,Main
Reach XY= 30
     1882799.876      630969.777     1882381.309      631299.741
     1881345.675      633822.318     1879563.708      635473.888
     1879207.645      636210.253     1878272.763      636528.196
     1877993.781      638688.612     1877342.228      639760.081
     1876705.987      640056.342      1876680.48      640845.519
     1876098.647      641357.833     1876425.967      642489.541
     1875523.704       643124.08     1874648.311      644690.588
     1874964.358      645590.239     1874212.314      646251.907
     1873043.486      646132.016     1872305.323      647080.247
     1872331.327      648061.513     1872028.386      647648.833
     1870367.013      647548.814     1871481.993      649339.721
     1870587.506      650562.352       1868621.5      650603.936
     1868644.057       651003.39      1869771.17      651795.406
     1869713.837      652208.751     1869071.232      652325.081
     1867634.968       651703.25     1867110.465      651781.378

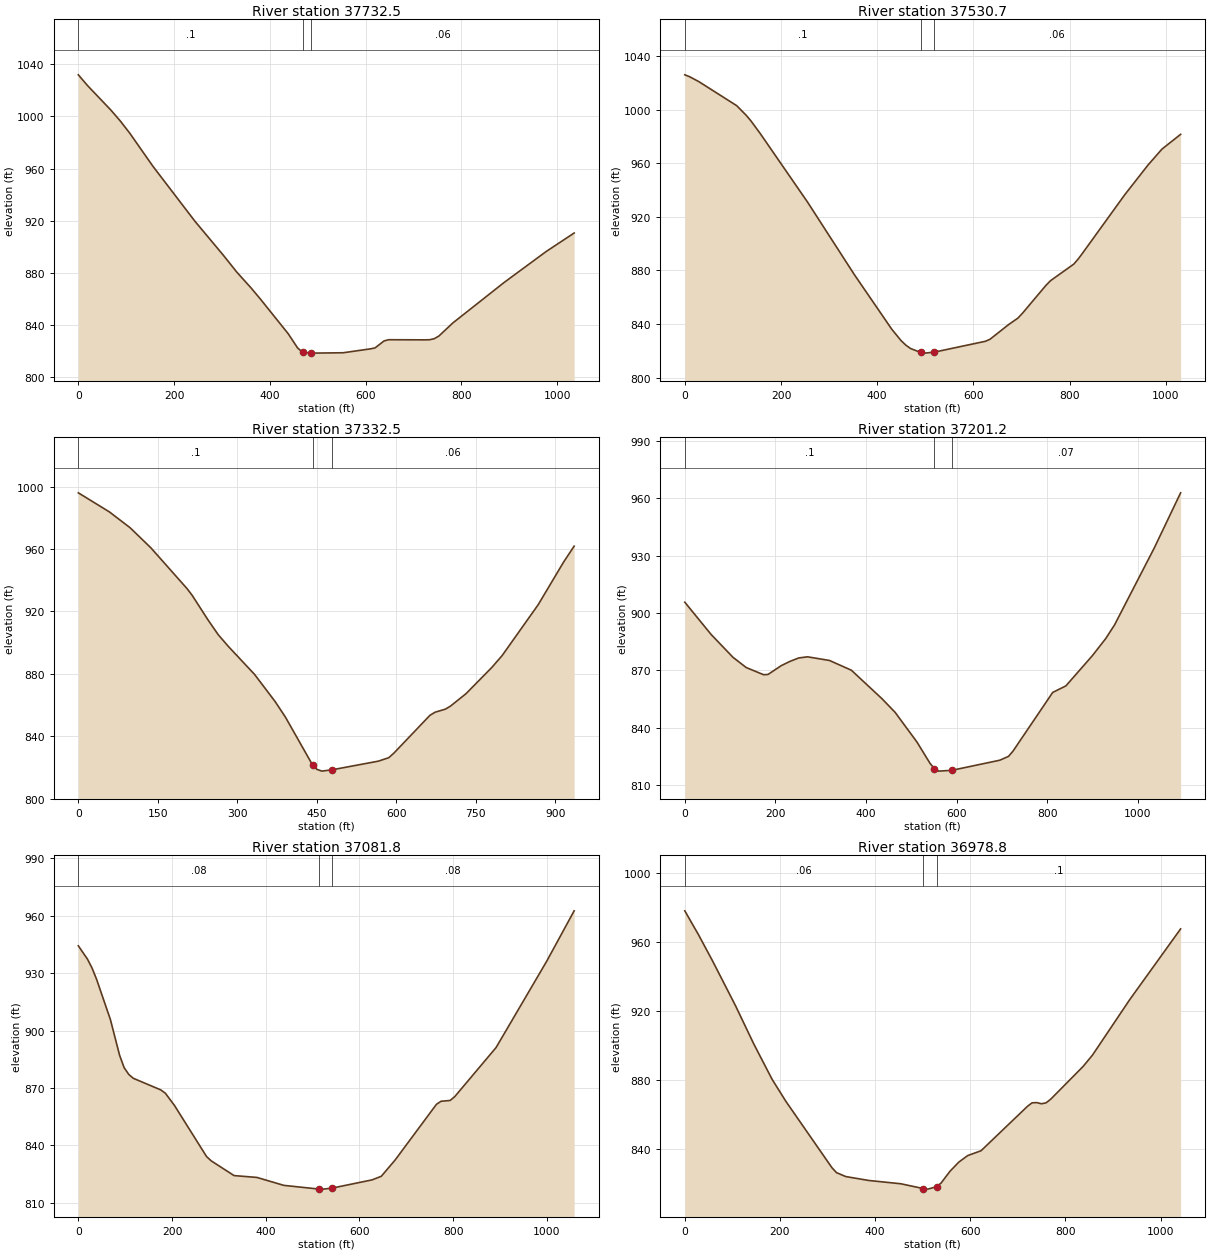
Type RM Length L Ch R = 1 ,37732.5 ,196.4,201.8,213.7
XS GIS Cut Line= 4
     1882395.405      630721.419     1882797.002      630979.355
     1883042.159      631052.911     1883341.651      631013.803
#Sta/Elev= 30
       0 1031.73    19.5 1023.38    68.2 1004.65    87.7  996.36   107.2  987.15
   155.8  961.69   243.5  919.61     302  893.95   331.2  880.53   360.4  868.68
   379.9  860.16   438.3  833.47   457.8  822.63   467.6  819.48   469.8  819.31
   484.8  818.66   486.8  818.64   553.1  818.92     610  821.91   619.5  822.62
   638.4  827.99   647.9   828.9   723.8   828.8   733.2  828.88     743  829.66
   752.7  831.68     782  841.75   889.1  872.75   976.8  896.43  1035.3  910.61
#Mann= 3 , 0 , 0
       0      .1       0   469.8    .045       0   484.8     .06       0
Bank Sta=469.8,484.8
XS Rating Curve= 0 ,0
Exp/Cntr=0.3,0.1

Type RM Length L Ch R = 1 ,37530.7 ,194.5,198.2,198.2
XS GIS Cut Line= 4
     1882340.364      630773.804     1882548.697      630995.158
     1882767.881      631229.533     1883039.148      631531.182
#Sta/Elev= 30
       0 1026.12     9.8 1024.75    29.4    1021   107.9 1003.08   127.5  995.96
   137.3   991.8   156.9  982.22     255  931.14   352.6   876.8   430.4  836.02
   449.8  827.51   459.6  824.19   469.3   821.7   490.1   818.8   498.5  818.26
   517.9  818.95   624.9  827.11   634.5  828.64   673.2  839.62   692.5  844.44
   702.1  848.14   750.4  868.76   760.1  872.35   808.4  884.71     818  888.69
   827.7  893.38   914.6  936.62   962.9  958.78   991.9  970.67  1030.6  981.67
#Mann= 3 , 0 , 0
       0      .1       0   490.1    .045       0   517.9     .06       0
Bank Sta=490.1,517.9
XS Rating Curve= 0 ,0
Exp/Cntr=0.3,0.1

Type RM Length L Ch R = 1 ,37332.5 ,141.3,131.3,124.3
XS GIS Cut Line= 3
     1882254.223      630840.946     1882506.212       631213.41
      1882829.89      631575.495
#Sta/Elev= 30
       0  996.01    58.7  983.76    97.8  973.59   136.9  960.73   205.3  934.52
   215.1  930.12   244.4  914.66     264  905.01   283.5  897.36   332.4  879.62
   371.5  862.08     391  852.03   439.9  822.69   442.2  821.77   449.7  818.77
   459.4  817.57   478.8  818.43   566.3  823.98   585.7   826.2   595.4  829.14
   663.4  853.38   673.1  855.35   692.5  857.31   702.2  859.28   731.4  867.23
     780  884.02   799.4   891.6   867.4   924.2   915.9  951.84   935.4  961.82
#Mann= 3 , 0 , 0
       0      .1       0   442.2    .045       0   478.8     .06       0
Bank Sta=442.2,478.8
XS Rating Curve= 0 ,0
Exp/Cntr=0.3,0.1

Type RM Length L Ch R = 1 ,37201.2 ,143,119.4,94.7
XS GIS Cut Line= 4
     1881882.898      631032.756     1882304.773        631227.2
     1882511.371      631350.464     1882825.824      631580.716
#Sta/Elev= 30
       0  905.62    58.1  888.74   106.4  876.78   135.5  871.44   164.5  868.59
   174.2  867.66   183.9  867.82   212.9  872.41   232.3  874.65   251.6  876.44
     271  877.03   319.4  875.13   367.8  870.02   435.5  855.08   464.5  847.94
   512.6  832.44   541.5  821.28   551.1  818.47   560.8   817.2   589.6  817.62
   695.5  822.91   714.8  824.92   724.6  827.64   812.3  858.37   841.5  861.82
     900  877.65   929.2  886.52   948.7  893.64  1036.4  933.91  1094.8  962.87
#Mann= 3 , 0 , 0
       0      .1       0   551.1    .045       0   589.6     .07       0
Bank Sta=551.1,589.6
XS Rating Curve= 0 ,0
Exp/Cntr=0.3,0.1

Type RM Length L Ch R = 1 ,37081.8 ,105.8,103,100.8
XS GIS Cut Line= 4
     1881840.581      631488.123     1882248.567      631442.984
      1882416.97      631361.387     1882820.181      631583.826
#Sta/Elev= 30
       0  944.34    19.6  937.33    29.3  932.71    39.1  926.73    68.4  905.83
      88  887.16    97.7  880.66   107.5  877.14   117.3  875.08   175.9  869.02
   185.7  867.28   205.2  860.87   273.6  834.19   283.4  831.95   332.3  824.22
   381.2  823.25   438.6   819.1   513.4  817.17   522.8  817.14   541.5  817.67
     627  821.98   646.6  823.87     676  832.35   764.2  861.46     774  863.06
   793.6   863.5   803.4  865.53   891.5  891.16   999.3  936.18  1058.1  962.62
#Mann= 3 , 0 , 0
       0     .08       0   513.4    .045       0   541.5     .08       0
Bank Sta=513.4,541.5
XS Rating Curve= 0 ,0
Exp/Cntr=0.3,0.1

Type RM Length L Ch R = 1 ,36978.8 ,103.6,120,136.7
XS GIS Cut Line= 4
     1881835.372       631613.08     1882299.348      631518.896
     1882429.122      631445.111     1882820.181      631597.021
#Sta/Elev= 30
       0  978.28      29  964.28      58  949.33   106.3  923.25   144.9   900.9
   183.6  880.22   212.6   867.4   309.2  828.88   318.8  825.99   338.2   823.7
   386.5  821.42   454.1   819.5   501.4   816.7   510.8  816.38   529.4  817.79
   538.8  819.95   557.4  826.76   576.1  832.13   594.7   835.9   622.7   838.7
   720.3  864.56     730  866.59   739.8  866.72   749.6  866.04   759.3  866.56
   769.1  868.68   837.4  887.81   856.9  894.33   934.9  926.49  1042.2  967.78
#Mann= 3 , 0 , 0
       0     .06       0   501.4    .045       0   529.4      .1       0
Bank Sta=501.4,529.4
XS Rating Curve= 0 ,0
Exp/Cntr=0.3,0.1

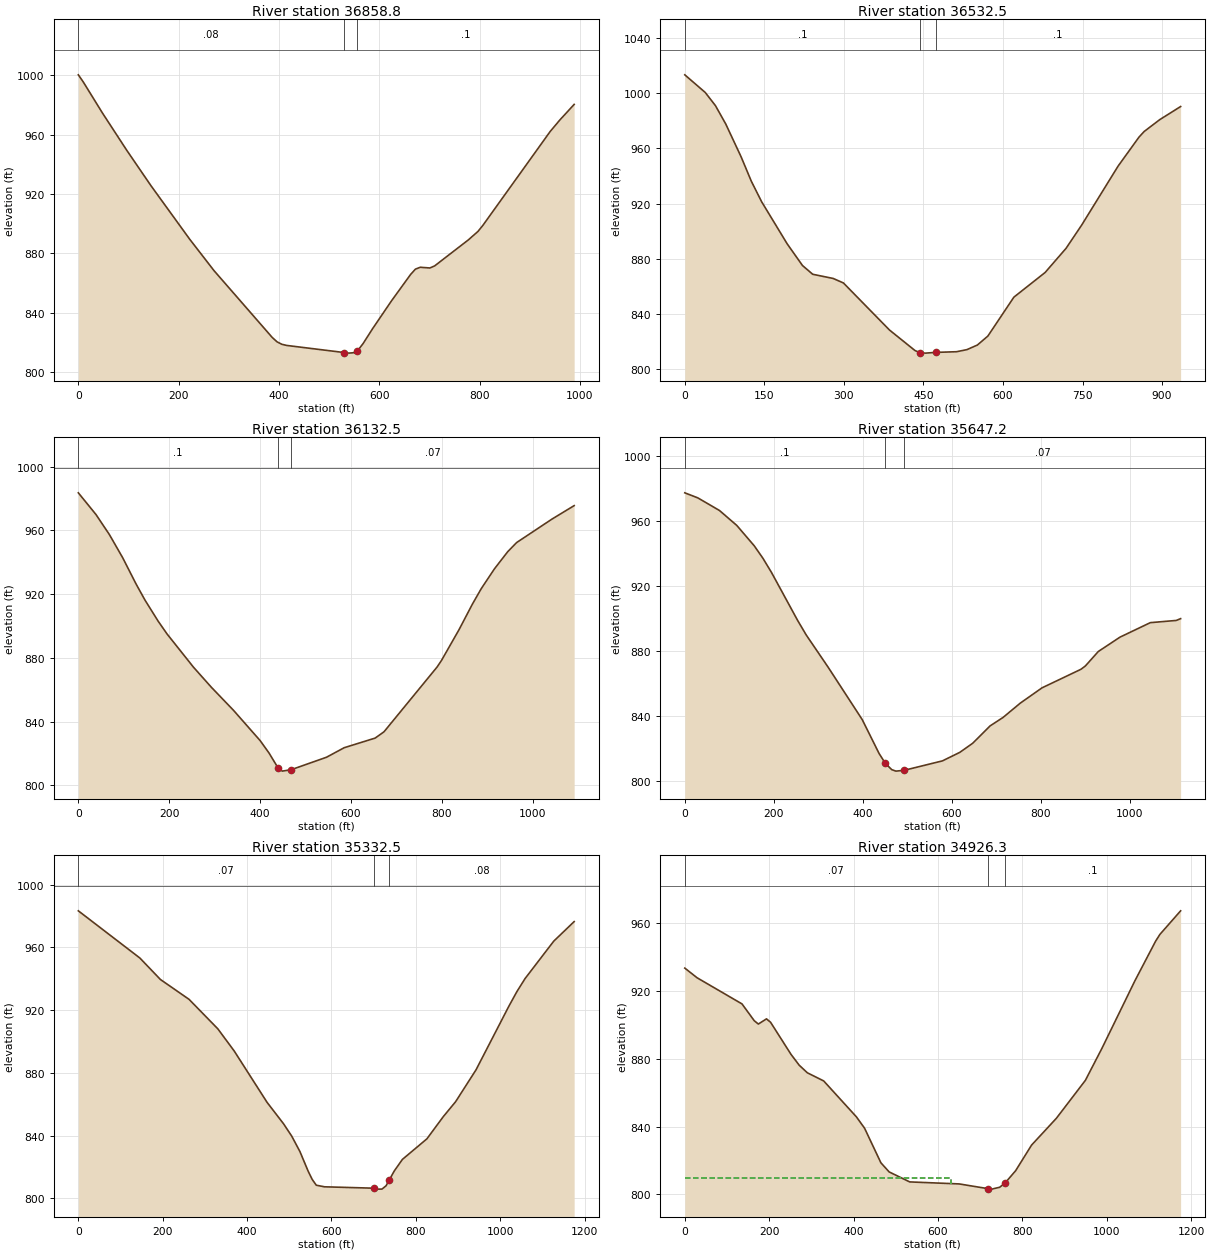
Type RM Length L Ch R = 1 ,36858.8 ,322.6,326.3,330.1
XS GIS Cut Line= 4
     1881781.596      631689.169      1882217.36      631601.495
     1882424.826       631621.46     1882752.951      631691.773
#Sta/Elev= 30
       0 1000.42     9.7  995.68    48.3  974.57    96.6  949.53   144.9  925.64
   222.2  889.53   270.6  868.39   386.5  823.41   396.2  820.42   405.8  818.77
   415.5     818   529.8  813.22   539.2  812.82   548.7   813.1   554.8  814.38
   558.2  815.09   567.7  819.25   586.6  829.27   624.5  848.13   662.5  865.88
   672.1  869.45   681.7   870.7   700.9  870.22   710.4  871.63   777.6  889.16
   796.7  894.85   806.3  898.84   940.6  962.18   959.7  969.88   988.5  980.48
#Mann= 3 , 0 , 0
       0     .08       0   529.8    .045       0   554.8      .1       0
Bank Sta=529.8,554.8
XS Rating Curve= 0 ,0
Exp/Cntr=0.3,0.1

Type RM Length L Ch R = 1 ,36532.5 ,387.2,400,409.2
XS GIS Cut Line= 3
     1881734.293      631784.082     1882175.522      631888.593
       1882637.3      632024.996
#Sta/Elev= 30
       0 1013.38    38.6 1000.57    57.9  990.98    77.2  977.74   106.1     954
   125.4  936.27   144.7  921.47     193  890.86   221.9  875.11   241.2  868.76
   279.8  865.72   299.1  862.46   385.9  828.36   434.1  813.44   443.8   811.9
   453.4  811.58   473.1  812.11   512.4   812.6     532  814.12   551.7  817.45
   571.4  823.92   620.5  852.16   679.4  870.05   718.8  887.53   748.2  904.35
     817  947.18   856.3  968.16   866.2   972.3   895.6   980.9   934.9  990.39
#Mann= 3 , 0 , 0
       0      .1       0   443.8    .045       0   473.1      .1       0
Bank Sta=443.8,473.1
XS Rating Curve= 0 ,0
Exp/Cntr=0.3,0.1

Type RM Length L Ch R = 1 ,36132.5 ,484.7,485.3,485.7
XS GIS Cut Line= 3
     1881655.963      631914.615     1882017.703      632196.814
     1882527.256      632571.981
#Sta/Elev= 30
       0  983.64      39  969.96    68.3  957.47    97.6  942.92   126.9  926.51
   146.4  916.44   175.7  903.07   195.2  895.06   253.8  874.05   292.8  861.57
   341.7  847.04   400.2  828.08   419.8  820.28   439.3  811.08     449  808.88
   468.5  809.77   546.4   817.6   585.4  823.59   653.5  829.63     673  833.59
   789.8  874.25   799.5  878.37   838.4  897.83   867.7  913.81   887.1  923.48
   916.3  935.98   945.5  946.72     965  952.42  1042.9  967.17  1091.6   975.6
#Mann= 3 , 0 , 0
       0      .1       0   439.3    .045       0   468.5     .07       0
Bank Sta=439.3,468.5
XS Rating Curve= 0 ,0
Exp/Cntr=0.3,0.1

Type RM Length L Ch R = 1 ,35647.2 ,316.7,314.7,314.9
XS GIS Cut Line= 4
     1881444.002      632331.898     1881742.534      632551.148
     1881890.103      632669.203     1882258.159      633084.134
#Sta/Elev= 30
       0  977.51    29.2  974.41      78  966.63     117   957.4     156  944.92
   175.4   937.3   194.9  928.47   253.4  899.06   272.9  890.02   321.7  870.37
   398.7  837.96   436.5  817.14  450.86  810.98   464.9  807.21   474.3  806.28
   493.2   806.8   578.8  812.58   617.8  817.81     647  823.46   685.9   834.1
   715.1  839.32     754  848.16   802.6  857.52   890.2  868.96     900  870.98
   929.1  879.89   977.8  888.72  1045.9  897.63  1104.3     899    1114  900.09
#Mann= 3 , 0 , 0
       0      .1       0  450.86    .045       0   493.2     .07       0
Bank Sta=450.86,493.2
XS Rating Curve= 0 ,0
Exp/Cntr=0.3,0.1

Type RM Length L Ch R = 1 ,35332.5 ,408.9,406.2,399.7
XS GIS Cut Line= 3
     1881143.431      632496.786     1881757.236      632890.611
     1882098.616      633177.394
#Sta/Elev= 30
       0  983.31   145.9  953.21   194.5  939.54   262.5  926.85   330.6  908.07
   369.5  893.91   447.3   861.2   486.2  847.58   505.6  839.73   525.1  829.87
   544.5  817.42   554.3  812.03     564  808.36   583.4  807.34   700.1  806.46
   709.8  805.86   719.6  805.88   729.3  807.99   736.8  811.64   748.7  817.41
     768   824.8   826.2  837.95     865  852.09   894.1  861.59   942.5  881.91
  1020.1  922.35  1039.4  931.81  1058.8  940.13  1126.7  963.96  1175.1  976.44
#Mann= 3 , 0 , 0
       0     .07       0   700.1    .045       0   736.8     .08       0
Bank Sta=700.1,736.8
XS Rating Curve= 0 ,0
Exp/Cntr=0.3,0.1

Type RM Length L Ch R = 1 ,34926.3 ,75.9,74.9,74.4
XS GIS Cut Line= 5
     1880823.986      633104.425     1881296.209      633149.563
     1881520.167      633170.397     1881622.598      633217.272
      1881969.82      633323.175
#Sta/Elev= 30
       0  933.31      29  927.63   135.5  912.22   164.6  902.32   174.3  900.36
   193.6  903.41   203.3   901.4   251.7   882.5   271.1  876.12   290.4  871.64
   329.2  866.84   406.6  845.71     426  839.02   464.7  818.64   484.2  813.27
     533  807.37   650.4  806.18   718.1  803.41   727.5  803.12   746.2  804.22
  758.72806.6654   783.8  813.89   821.8  829.06   880.6  844.85   949.3  867.19
   988.6  886.08    1067     926  1116.1  949.33  1125.9  953.15    1175  967.04
#Mann= 3 , 0 , 0
       0     .07       0   718.1    .045       0  758.72      .1       0
#XS Ineff= 2 , 0
          629.73  809.71
Permanent Ineff=
       F       F
Bank Sta=718.1,758.72
XS Rating Curve= 0 ,0
Exp/Cntr=0.3,0.1

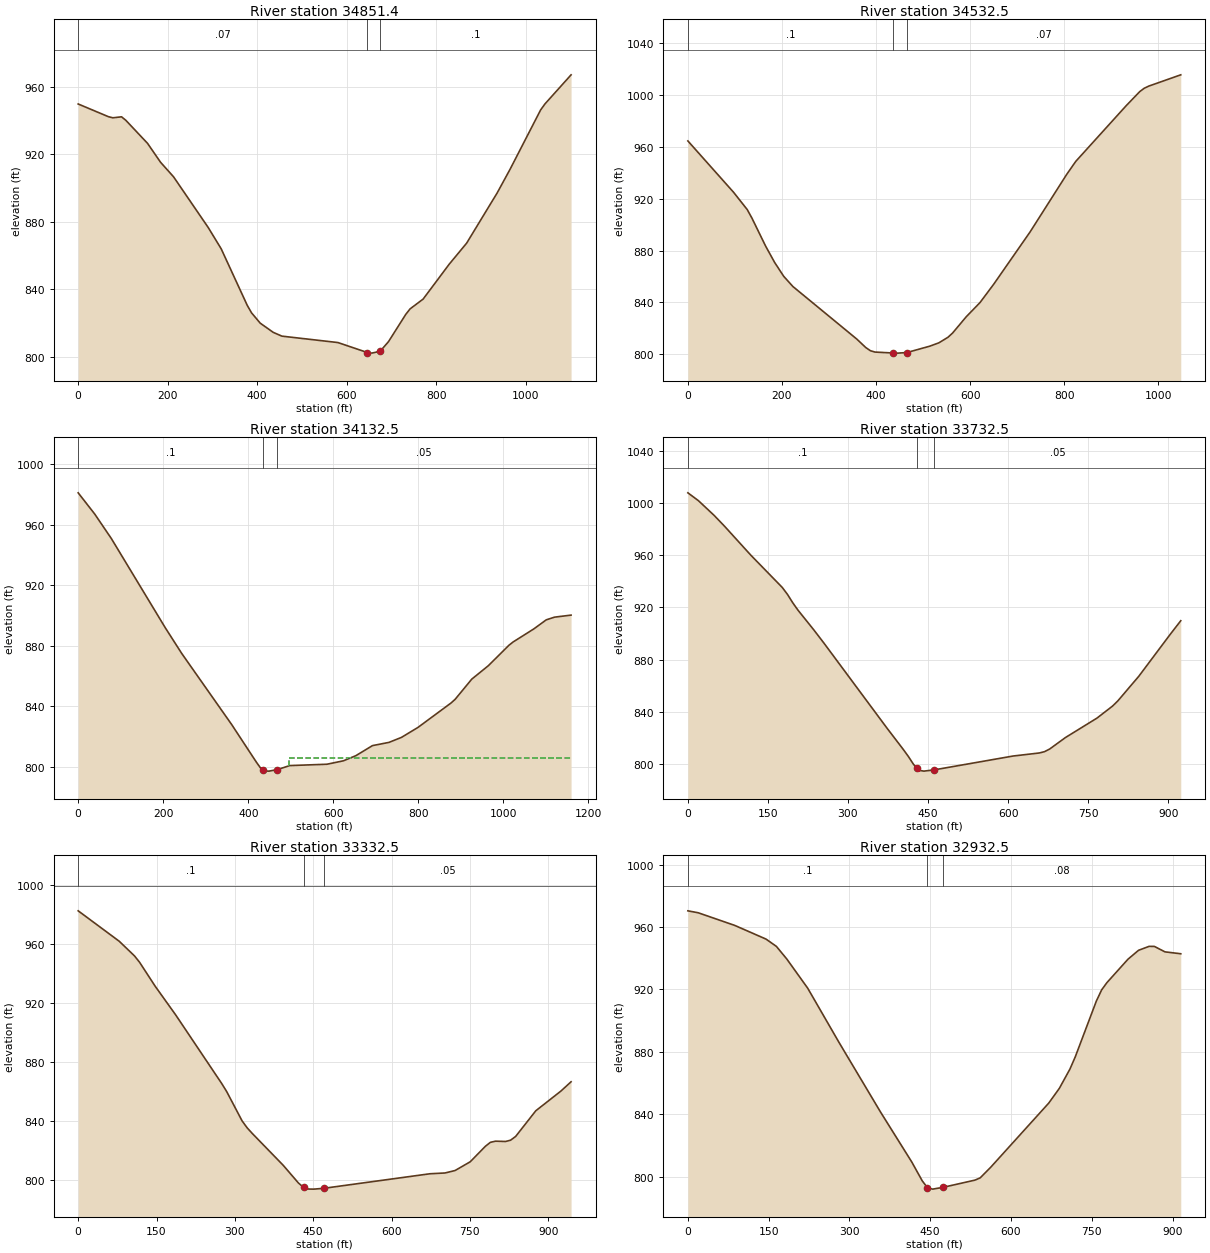
Type RM Length L Ch R = 1 ,34851.4 ,318.5,318.9,318.8
XS GIS Cut Line= 4
     1880914.264      633168.661     1881463.309      633226.495
     1881610.445      633290.297     1881972.424       633432.55
#Sta/Elev= 30
       0  949.66    67.8  942.11    77.5  941.48    96.9  942.06   106.5  939.99
     155  926.35     184  915.18   213.1  906.55   290.6  876.52   319.6   863.9
   377.7   830.5   387.4  826.01   406.8   819.9   435.8  814.46   455.2  812.22
   580.4  808.42   646.4   802.5   655.8  802.16   674.7  803.23   693.6  809.03
   731.9  825.06   741.6  828.34   770.8  834.15   829.1  854.81     868  867.26
   936.1  896.93   965.3  911.12  1033.3  946.11    1043  949.68  1101.4  966.92
#Mann= 3 , 0 , 0
       0     .07       0   646.4    .045       0   674.7      .1       0
Bank Sta=646.4,674.7
XS Rating Curve= 0 ,0
Exp/Cntr=0.3,0.1

Type RM Length L Ch R = 1 ,34532.5 ,389.2,400,413.7
XS GIS Cut Line= 3
     1881075.508      633389.839     1881491.293      633576.702
      1882032.32      633815.796
#Sta/Elev= 30
       0  964.52      97  924.98   126.1  911.62   135.8  905.27   164.9  883.66
   184.3  870.88   203.7  860.13   223.1   852.3   358.9  811.76   378.2  805.16
     388  802.76   397.6  801.73   436.4     801   446.2  800.91   465.5  801.37
     514  806.27   533.4  808.85   552.8  813.16   562.5  816.39   591.6  828.98
   620.7  839.86   649.8  853.99   727.4  894.47   804.9  938.67   824.3  948.78
     931  991.53   960.1 1002.51   969.8 1005.15   979.5 1006.82  1047.4  1015.5
#Mann= 3 , 0 , 0
       0      .1       0   436.4    .045       0   465.5     .07       0
Bank Sta=436.4,465.5
XS Rating Curve= 0 ,0
Exp/Cntr=0.3,0.1

Type RM Length L Ch R = 1 ,34132.5 ,397.1,400,397.2
XS GIS Cut Line= 3
     1880972.577      633532.645     1881258.676      633890.844
     1881624.334      634488.539
#Sta/Elev= 30
       0  981.06      39  967.01      78  950.87   204.8  891.96   243.8  874.86
   360.9  828.06   419.4  803.05   429.2  799.22  434.22798.2574   438.9  797.36
   448.7  797.28   468.2  798.27   497.4  800.94   584.9  801.83   623.9   804.1
   653.1   807.5     692  814.12   730.9  816.26   760.1  819.54     799  826.13
   876.9  842.29   886.6  844.75   925.6  858.04   964.5  866.89  1013.1  880.44
  1022.9  882.59  1071.5   891.2  1100.7  897.18  1120.2  898.96  1159.1  900.31
#Mann= 3 , 0 , 0
       0      .1       0  434.22    .045       0   468.2     .05       0
#XS Ineff= 2 , 0
                          496.46          806.07
Permanent Ineff=
       F       F
Bank Sta=434.22,468.2
XS Rating Curve= 0 ,0
Exp/Cntr=0.3,0.1

Type RM Length L Ch R = 1 ,33732.5 ,419.5,400,388.5
XS GIS Cut Line= 3
     1880687.277      633715.294     1880928.132      634097.863
     1881221.628      634466.981
#Sta/Elev= 30
       0 1008.02    19.7 1002.02    49.1  990.74    68.8  982.33   117.9  960.16
   176.9  935.34   186.7  929.98   196.6  923.53   206.4  917.87   235.9   902.8
   255.5   892.3   373.4  827.14   402.9  811.33   412.8  805.76   422.6  799.62
  428.75796.6705   432.4  794.92   442.2  794.27   461.9  795.26   609.3  805.86
   658.4   808.2   668.2   809.2     678  811.26   707.5  820.06   766.5  834.97
   795.9  844.27   805.8  848.27   845.1   867.2     904  899.42   923.6  909.78
#Mann= 3 , 0 , 0
       0      .1       0  428.75    .045       0   461.9     .05       0
Bank Sta=428.75,461.9
XS Rating Curve= 0 ,0
Exp/Cntr=0.3,0.1

Type RM Length L Ch R = 1 ,33332.5 ,390.4,400,405.7
XS GIS Cut Line= 3
     1880241.093      634330.904     1880687.565       634396.59
     1881153.492      634556.317
#Sta/Elev= 30
       0  982.38    78.5  961.82   107.9  951.85   117.7  947.49   147.2  931.48
   186.4   912.1   274.7  865.59   284.5  859.98   313.9   840.2   323.7  835.46
   333.6  831.64   392.4  810.25   421.8  798.18   431.7  795.19   441.5   794.1
   451.3  794.05   470.6  794.62   673.4  804.44   702.4  804.98   721.7  806.64
   750.7  812.56   779.6     823   789.3  825.71     799   826.5   818.3  826.29
   827.9  827.15   837.6  829.68   876.2  847.06   924.5  860.46   943.8   866.7
#Mann= 3 , 0 , 0
       0      .1       0   431.7    .045       0   470.6     .05       0
Bank Sta=431.7,470.6
XS Rating Curve= 0 ,0
Exp/Cntr=0.3,0.1

Type RM Length L Ch R = 1 ,32932.5 ,256.2,262.7,267.1
XS GIS Cut Line= 3
     1880150.037      634487.273     1880535.026      634729.031
     1880902.613      635006.523
#Sta/Elev= 30
       0  970.43    19.3  969.17      87  961.08   145.1   952.3   164.4  947.61
   183.8  939.47   222.5  920.81   280.5  886.11   357.9  841.27   415.9  809.24
   435.3  797.16   444.9  792.83   454.6  791.92   474.2   793.1     533  797.69
   542.8  799.15   562.4  805.99   670.2  847.16   689.8  856.59   709.4  868.92
   719.2  876.68   758.4   912.5   768.2  919.68     778  924.34   817.2   939.4
   836.8  945.11   856.4  947.64   866.2   947.6   885.8  944.12   915.2  942.89
#Mann= 3 , 0 , 0
       0      .1       0   444.9    .045       0   474.2     .08       0
Bank Sta=444.9,474.2
XS Rating Curve= 0 ,0
Exp/Cntr=0.3,0.1

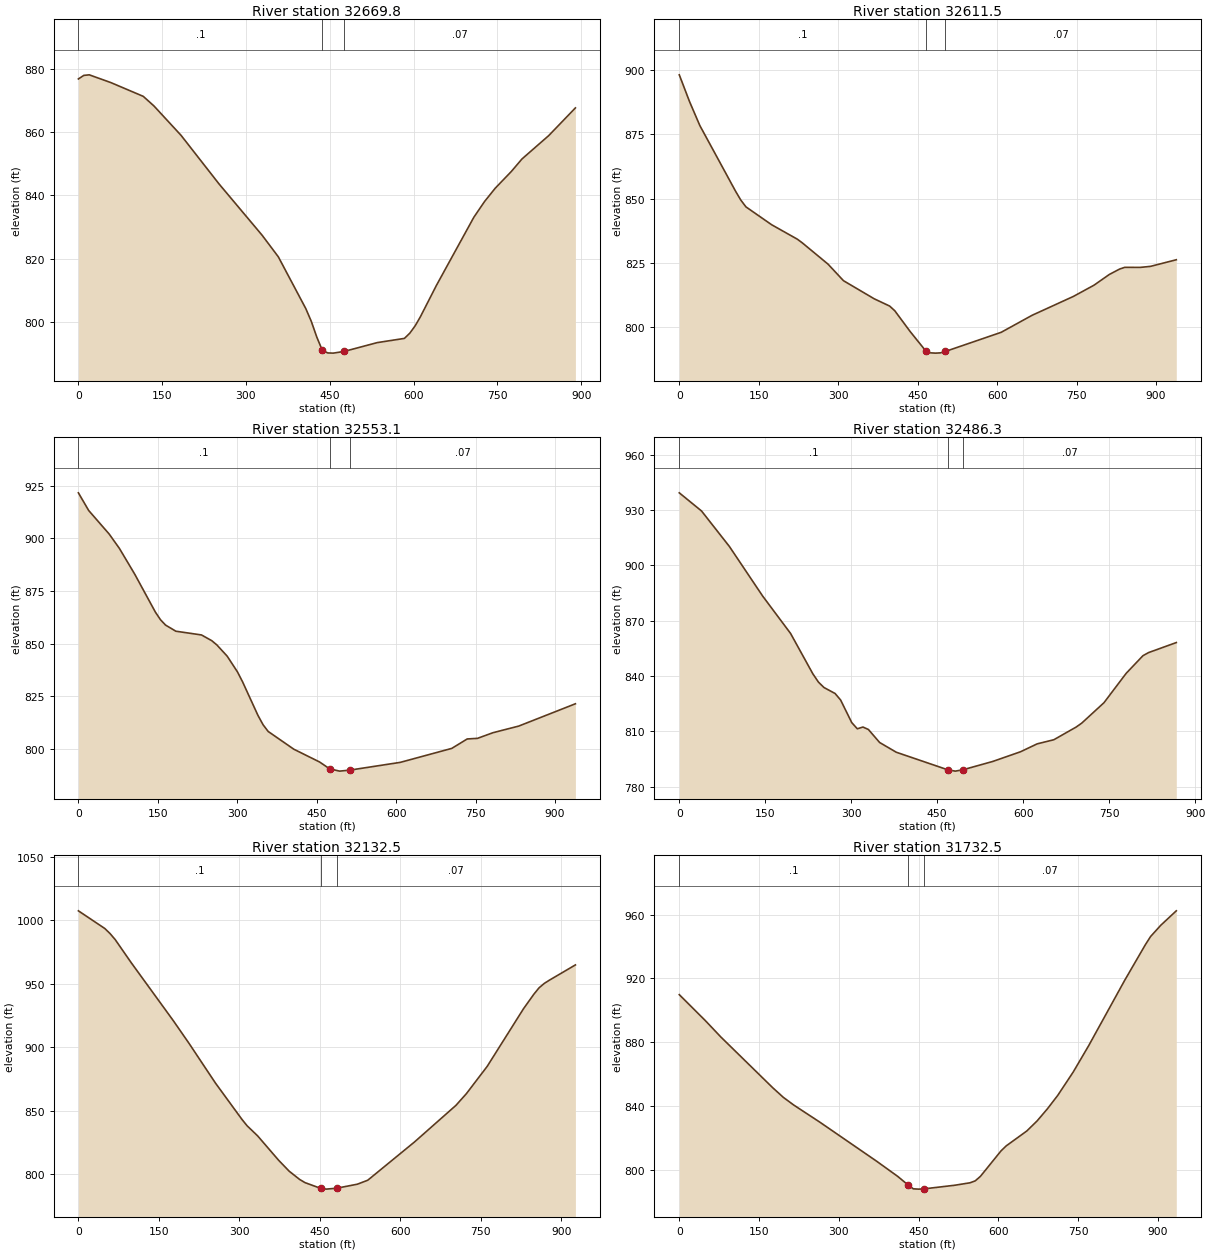
Type RM Length L Ch R = 1 ,32669.8 ,58.5,58.4,58.9
XS GIS Cut Line= 4
     1880019.733      634625.258     1880297.511      634850.952
     1880434.663      635005.466     1880644.733       635253.73
#Sta/Elev= 30
       0   876.9     9.7  878.02    19.4   878.2      58  875.75   116.1  871.39
   135.4  868.32   183.8  859.04   251.5  843.72   328.9  827.42   357.9  820.59
   407.1  804.19   416.9  800.17   426.8  795.16   436.6     791   446.4  790.16
   456.3   790.1     476  790.65     535  793.43   583.6  794.76   593.2   796.4
   602.8  798.73   612.3  801.64     641  811.57     708  833.14   727.1   838.1
   746.2  842.31     775   847.6   794.1  851.57   841.9  858.95   889.7  867.73
#Mann= 3 , 0 , 0
       0      .1       0   436.6    .045       0     476     .07       0
Bank Sta=436.6,476
XS Rating Curve= 0 ,0
Exp/Cntr=0.3,0.1

Type RM Length L Ch R = 1 ,32611.5 ,57.4,58.3,58.6
XS GIS Cut Line= 4
      1879945.08      634656.942     1880307.059      634948.609
     1880368.257      635020.223     1880567.042       635343.14
#Sta/Elev= 30
       0  898.09    19.4  887.68    38.7  878.44   106.5  852.81   116.2  849.45
   125.9  846.82   174.3   839.9   222.8  834.29   232.4  832.83   280.9  824.58
   309.9  818.18     368  811.14   397.1  808.32   406.8  806.51   435.8  798.45
   464.9  791.02   474.3  790.16   483.7  790.05   493.1  790.15   502.5  790.71
   607.7  798.13     666  804.73   743.8  812.04   782.7  816.39   811.9  820.59
   831.3  822.69     841  823.35   870.2  823.33   889.6  823.73   938.3   826.3
#Mann= 3 , 0 , 0
       0      .1       0   464.9    .045       0   502.5     .07       0
Bank Sta=464.9,502.5
XS Rating Curve= 0 ,0
Exp/Cntr=0.3,0.1

Type RM Length L Ch R = 1 ,32553.1 ,69.3,66.8,64.3
XS GIS Cut Line= 4
     1879900.809        634693.4     1880262.788      634985.067
     1880323.986      635056.682     1880522.771      635379.598
#Sta/Elev= 30
       0  921.67    19.4   913.3    58.1  902.11    77.5  895.26   106.5     883
   145.3  865.07     155  861.42   164.6  858.88     184  855.98   232.4   854.2
   251.8  851.48   261.5  849.45   280.9  844.13   300.2  836.72   309.9  831.99
     339  816.02   348.6   811.6   358.3  808.39   406.8  799.95   455.2  793.92
   474.3  790.66   493.1  789.56     512  790.02   607.7  793.72   704.9  800.35
   734.1  804.83   753.5  805.12   782.7   807.8   831.3  810.94   938.3  821.53
#Mann= 3 , 0 , 0
       0      .1       0   474.3    .045       0     512     .07       0
Bank Sta=474.3,512
XS Rating Curve= 0 ,0
Exp/Cntr=0.3,0.1

Type RM Length L Ch R = 1 ,32486.3 ,351.5,353.8,357.2
XS GIS Cut Line= 4
     1879868.691      634778.036     1880184.663       635003.73
     1880299.247      635113.105     1880458.969      635390.883
#Sta/Elev= 30
       0  939.27    38.8  929.44    87.4  910.22   145.6  883.29   194.2  863.08
     233  841.25   242.7  836.78   252.4  833.82   271.8  830.58   281.5  827.03
   300.9   814.8   310.6  811.46   320.4  812.41     330  811.07   349.5  804.04
   378.6  798.76  468.61789.2299   481.5  788.53  494.41  789.23   546.7  793.75
   595.2     799   624.4   803.3   653.5  805.54   692.4   812.4   702.1  814.52
   740.9  825.58   779.7  841.52   808.9  851.04   818.6  852.72   867.1  858.17
#Mann= 3 , 0 , 0
       0      .1       0  468.61    .045       0  494.41     .07       0
Bank Sta=468.61,494.41
XS Rating Curve= 0 ,0
Exp/Cntr=0.3,0.1

Type RM Length L Ch R = 1 ,32132.5 ,396.3,400,392.8
XS GIS Cut Line= 3
     1879640.849      634860.127     1879956.813      635209.903
     1880230.302      635573.081
#Sta/Elev= 30
       0  1007.4    49.1   993.5    58.9  989.51    68.7  984.66    98.2  966.66
   176.8  920.85   206.2  902.91   255.3   871.7   304.4  843.22   314.2  838.05
   333.9  830.07   373.2  810.76   392.8  802.18   412.4  795.65   422.3  793.18
   451.7  788.63   461.5  788.07     481  788.77   519.7  791.95   539.1  795.07
   626.1   825.2   703.5  854.11   722.9   863.3   761.6  884.78   829.3  930.23
   848.6  941.68   858.3  946.72     868  950.19   877.6  952.76     926  964.77
#Mann= 3 , 0 , 0
       0      .1       0   451.7    .045       0     481     .07       0
Bank Sta=451.7,481
XS Rating Curve= 0 ,0
Exp/Cntr=0.3,0.1

Type RM Length L Ch R = 1 ,31732.5 ,376.3,362.2,355.6
XS GIS Cut Line= 3
     1879380.459      635051.226     1879626.138      635427.967
     1880017.499      635713.834
#Sta/Elev= 30
       0  909.74    48.9  893.49    78.2  883.17     176  851.26   195.6  845.33
   215.1  840.53     264  829.83   371.6  805.14   410.7  795.75   430.2  790.35
     440  787.96   449.8  787.77   459.5  787.91   517.6  790.19   546.7  791.75
   556.4  792.96   566.1  795.76   604.9  811.77   614.6  814.88   653.3  824.22
   672.7  830.54   692.1  838.14   711.5  846.55   740.6  861.21   769.6   877.7
   837.5   918.8   876.3   941.1     886  946.18   905.3  953.29   934.4  962.32
#Mann= 3 , 0 , 0
       0      .1       0   430.2    .045       0   459.5     .07       0
Bank Sta=430.2,459.5
XS Rating Curve= 0 ,0
Exp/Cntr=0.3,0.1

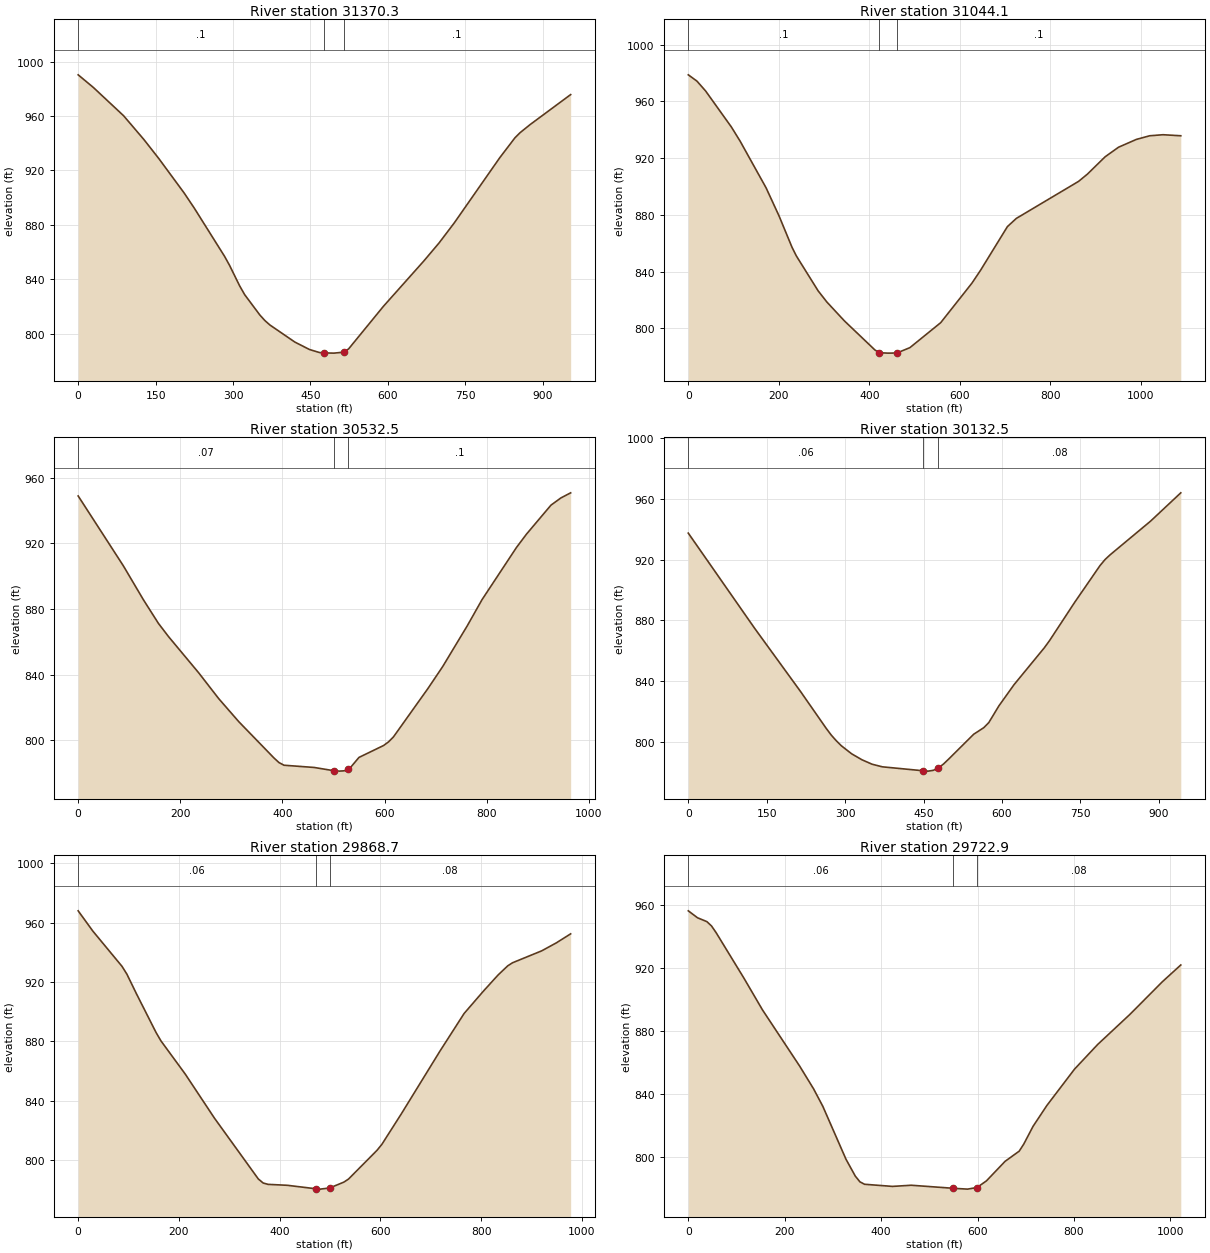
Type RM Length L Ch R = 1 ,31370.3 ,322.7,326.2,359.3
XS GIS Cut Line= 4
     1879041.311      635612.339     1879435.098      635687.324
     1879587.441      635739.407      1879935.19      635921.057
#Sta/Elev= 30
       0  990.29    29.3  981.05      88  960.24   127.1  942.86   156.4  928.69
   205.3  903.47   224.9  892.38   283.5     857   293.3   850.3   312.9  835.19
   322.6  828.74     352   813.8   361.8   809.7   371.5  806.46   419.8  793.91
   448.2  788.44   467.2  786.25   476.6  785.91   495.6  785.78   514.5  786.49
     524  788.89   591.3  820.12   669.8  853.53   699.2  866.72   728.6  881.43
   816.9  929.42   846.3  944.03   856.1  947.74   875.7  953.74   954.2  975.77
#Mann= 3 , 0 , 0
       0      .1       0   476.6    .045       0   514.5      .1       0
Bank Sta=476.6,514.5
XS Rating Curve= 0 ,0
Exp/Cntr=0.3,0.1

Type RM Length L Ch R = 1 ,31044.1 ,440.3,511.6,438.6
XS GIS Cut Line= 4
     1879011.052      635699.911     1879203.761      635840.536
     1879462.441      635970.744     1879902.459      636316.816
#Sta/Elev= 30
       0  978.75    19.1  974.32    38.2   967.4    95.4  941.88   114.5  932.01
   171.8  899.14   200.4  879.37     229  857.33   238.6  851.17   286.8  826.53
   306.1  818.64   344.8  805.35   412.3  784.83     422  782.88   441.3   782.6
   460.6  782.66   489.6  786.47   557.6  804.06   626.4  831.83     646  841.16
     705  871.77   724.6  877.53   862.1  903.63   881.7  908.76     921  921.02
   950.5  927.73   989.8  933.22  1019.2  935.79  1048.7  936.53    1088   935.8
#Mann= 3 , 0 , 0
       0      .1       0     422    .045       0   460.6      .1       0
Bank Sta=422,460.6
XS Rating Curve= 0 ,0
Exp/Cntr=0.3,0.1

Type RM Length L Ch R = 1 ,30532.5 ,387.9,400,402.5
XS GIS Cut Line= 3
     1878933.042      635762.562     1879185.103      636218.556
     1879338.353      636634.576
#Sta/Elev= 30
       0  948.95    88.5  906.33   127.8  885.63   157.3  871.18     177  863.16
   235.9  841.14   275.3  825.33   314.6  811.28   383.4  789.18   393.2  786.38
   403.1  784.74     462  783.39   501.4  781.36   511.2  781.15     521  781.34
   528.5  782.18   530.7  782.42   549.9  789.51   598.1  796.78   607.8     799
   617.4  802.02   684.9  831.52   713.8  844.91     762   869.8   790.9  885.74
   858.4  917.58   877.6  925.55   925.8  943.32   945.1   947.7   964.4  950.85
#Mann= 3 , 0 , 0
       0     .07       0   501.4    .045       0   528.5      .1       0
Bank Sta=501.4,528.5
XS Rating Curve= 0 ,0
Exp/Cntr=0.3,0.1

Type RM Length L Ch R = 1 ,30132.5 ,275,263.8,255.4
XS GIS Cut Line= 3
     1878827.404      635783.447     1878814.527       636242.07
     1878903.215      636716.897
#Sta/Elev= 30
       0  937.45   126.9  874.71   214.8  832.99   263.6  808.83   273.3  804.38
   283.1  800.56   292.8  797.25   312.4  791.99   331.9  788.09   351.4  785.13
     371  783.41     449  780.81   458.8  780.57   468.5  781.09   478.1  782.66
   487.8  785.18   497.4  788.33   545.8  804.89   565.1  809.22   574.7  812.59
     594  823.59     623  837.59     681  861.94   690.7  866.54     739  891.89
   787.3  916.04   796.9  920.01   806.6  923.14   883.9  945.32   941.8  964.02
#Mann= 3 , 0 , 0
       0     .06       0     449    .045       0   478.1     .08       0
Bank Sta=449,478.1
XS Rating Curve= 0 ,0
Exp/Cntr=0.3,0.1

Type RM Length L Ch R = 1 ,29868.7 ,136.6,145.9,155.1
XS GIS Cut Line= 4
     1878528.761       635844.16     1878561.313      636239.125
     1878641.608      636397.545     1878809.699      636764.557
#Sta/Elev= 30
       0  967.95      29  954.35      87  930.52    96.7  925.27     116  911.79
   154.7  885.84   164.3  880.26   212.6  857.83   270.6   828.1   357.6  787.11
   367.3  784.37     377  783.47     415  782.85   471.1  780.53   480.4  780.26
   499.1  781.02   527.2  784.95   536.5  787.01   593.1  806.39   602.8  810.44
   641.2  830.88   718.1  873.32   766.1  898.72   804.6  913.86   833.4  924.63
   852.6  930.82   862.2  932.92   919.9  940.93   948.8  946.27   977.6  952.43
#Mann= 3 , 0 , 0
       0     .06       0   471.1    .045       0   499.1     .08       0
Bank Sta=471.1,499.1
XS Rating Curve= 0 ,0
Exp/Cntr=0.3,0.1

Type RM Length L Ch R = 1 ,29722.9 ,43.9,45.9,53.2
XS GIS Cut Line= 4
     1878456.278      635857.615     1878499.681      636269.073
     1878518.778      636531.226     1878708.014       636819.42
#Sta/Elev= 30
       0  956.43    19.2  952.01    38.5  949.58    48.1  946.85    57.7  942.59
   115.5  913.64     154  893.49   230.9  857.91   259.8  843.46     279  832.34
   327.1  798.73   346.4  788.02     356   784.4   365.6  782.86   423.5  781.51
   462.4  782.24     550   780.3   579.2  779.78   598.7  780.81   618.2  784.98
   657.1  797.44   686.2  803.86   695.7  808.33   714.9  819.58   743.6  832.84
   801.1  855.97     849  871.59     916  890.73     983  911.36  1021.4  922.06
#Mann= 3 , 0 , 0
       0     .06       0     550    .045       0   598.7     .08       0
Bank Sta=550,598.7
XS Rating Curve= 0 ,0
Exp/Cntr=0.3,0.1

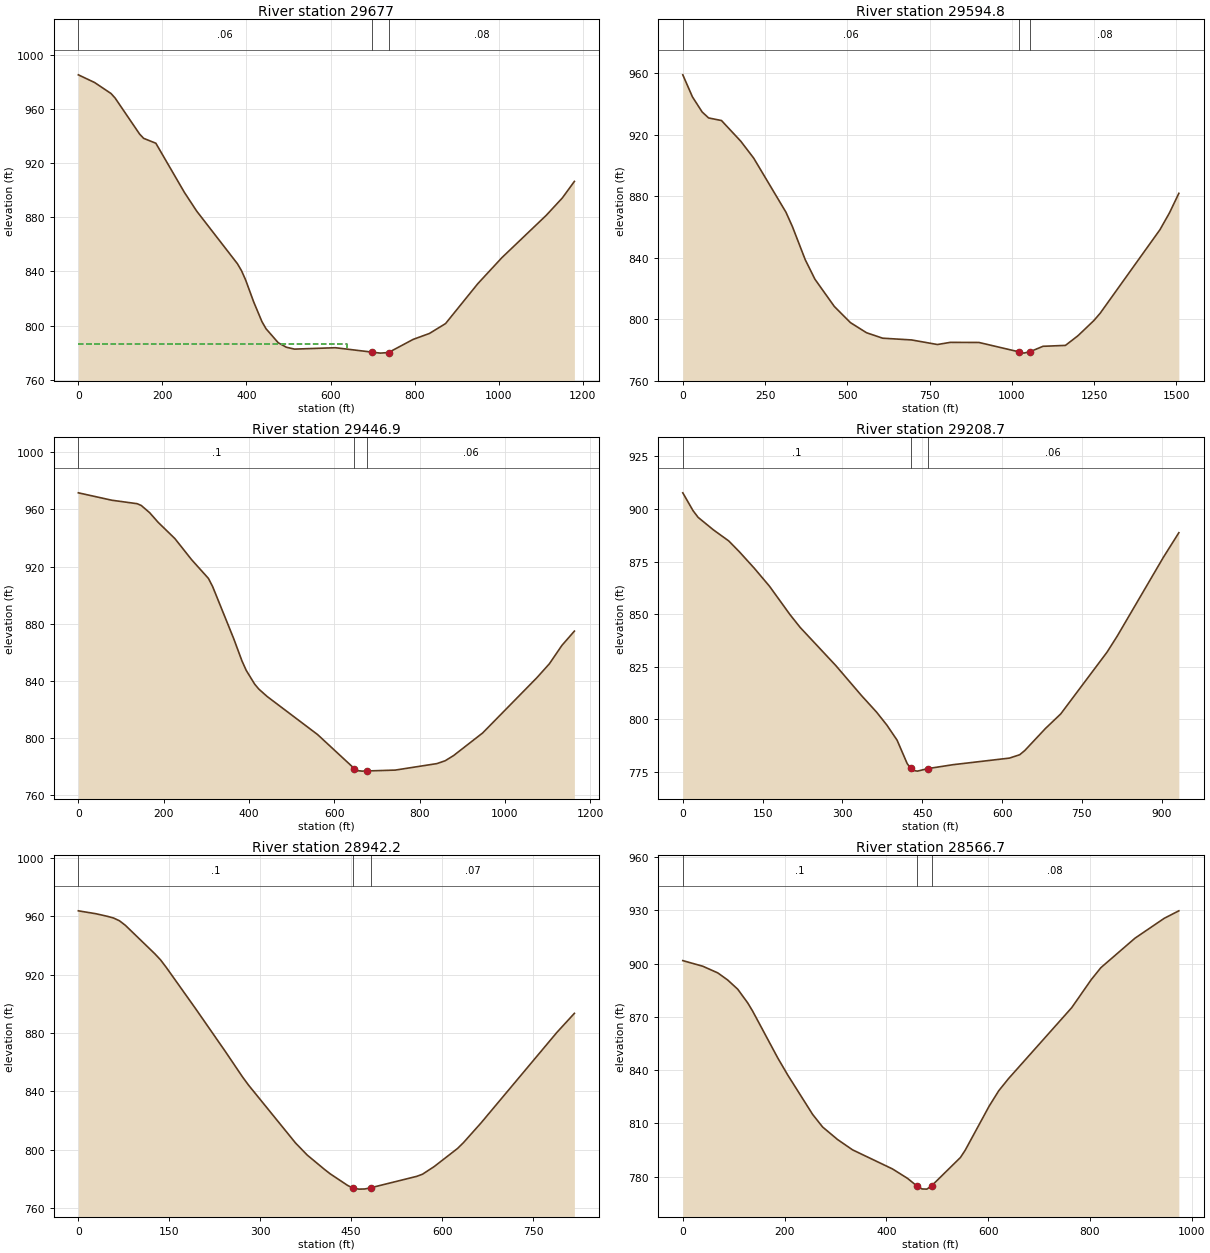
Type RM Length L Ch R = 1 ,29677   ,84.7,82.2,74.1
XS GIS Cut Line= 4
     1878398.986       635725.67     1878458.014      636295.115
     1878477.111      636557.267     1878666.348      636845.462
#Sta/Elev= 30
       0  985.12    38.8  979.42    77.6  971.36    87.3  968.07   145.6  941.47
   155.2  938.27   184.4  934.62   252.3  898.36   281.4  884.61   378.4  845.73
   388.1  840.62   397.8  833.86   417.2  817.48   436.6   803.1   446.4  797.76
   475.5   787.4   494.9  784.06   514.3  782.68   611.4  783.71     699  780.45
   718.5  779.72     738  780.18   796.4  789.84   835.3  794.24   873.6  801.53
   950.3  830.97  1007.7   850.2  1113.1  881.41  1151.4  894.24  1180.1  906.46
#Mann= 3 , 0 , 0
       0     .06       0     699    .045       0     738     .08       0
#XS Ineff= 2 , 0
          638.63  786.79
Permanent Ineff=
       F       F
Bank Sta=699,738
XS Rating Curve= 0 ,0
Exp/Cntr=0.3,0.1

Type RM Length L Ch R = 1 ,29594.8 ,165.3,147.9,130.7
XS GIS Cut Line= 5
      1877609.49      636234.351     1878383.361      636218.726
     1878400.723      636343.726      1878419.82      636605.879
     1878609.056      636894.073
#Sta/Elev= 30
       0  959.03    29.4  944.65    58.8  934.86    78.4  930.97   117.6  929.28
   176.4  915.77   215.6  904.77   313.5  869.63   333.1  860.28   372.3  838.63
   401.7  825.97   460.5  808.27   509.5  797.74   558.5  791.14   607.5  787.59
   695.6  786.45     774  783.47   812.9  784.87   900.2  784.81 1022.03778.6884
  1036.5  777.87    1056  778.86  1094.9  782.31  1163.1   782.9  1201.4  789.24
  1249.3  799.03  1268.4  803.76  1450.4  858.22  1479.1  869.09  1507.8  881.88
#Mann= 3 , 0 , 0
       0     .06       0 1022.03    .045       0    1056     .08       0
Bank Sta=1022.03,1056
XS Rating Curve= 0 ,0
Exp/Cntr=0.3,0.1

Type RM Length L Ch R = 1 ,29446.9 ,254.4,238.3,221.1
XS GIS Cut Line= 4
     1877639.004      636431.833     1878208.448      636471.764
     1878329.976      636579.403     1878597.337      636916.208
#Sta/Elev= 30
       0  971.57    78.7  966.38   137.8  963.97   147.6   962.7   167.3  957.65
     187  950.97   226.4  939.55   265.7  924.75   305.1  911.67     315  905.92
   364.2  869.63   383.8  853.89   393.7  847.33   413.4  837.74   423.2  834.24
   442.9  829.03     561  802.43   647.2  778.62   656.8  777.09   666.3  776.84
   675.9  776.94     743  777.56   840.7   782.1   860.2  784.09   879.8   787.7
   948.2  803.58  1075.2  842.19  1104.6  851.97  1133.9   864.8  1163.2  874.81
#Mann= 3 , 0 , 0
       0      .1       0   647.2    .045       0   675.9     .06       0
Bank Sta=647.2,675.9
XS Rating Curve= 0 ,0
Exp/Cntr=0.3,0.1

Type RM Length L Ch R = 1 ,29208.7 ,267.9,266.4,264.8
XS GIS Cut Line= 4
       1877761.4      636781.226     1878095.601      636750.844
     1878325.636      636753.014     1878627.285      636961.347
#Sta/Elev= 30
       0  907.72    19.2  899.26    28.8  896.05    57.5  890.11    86.3  884.85
   105.5   879.9   134.2   871.9     163  863.27   201.4  849.81   220.5  843.72
   287.6  825.54   335.6  811.35   364.3  803.37   383.5  797.24   402.7  790.07
   421.8  778.87  428.27776.7605   431.4  775.74     441  775.34   460.2  776.53
   508.1  778.41   613.9  781.54   633.2  783.14   642.8  785.17   681.4  795.59
   710.3  802.57   797.2  831.91   816.5   839.6   903.3  877.12   932.2  888.74
#Mann= 3 , 0 , 0
       0      .1       0  428.27    .045       0   460.2     .06       0
Bank Sta=428.27,460.2
XS Rating Curve= 0 ,0
Exp/Cntr=0.3,0.1

Type RM Length L Ch R = 1 ,28942.2 ,367.9,375.5,382.9
XS GIS Cut Line= 4
     1877836.163      637088.738     1878195.427       637009.09
     1878375.549       636998.24     1878644.646      637017.771
#Sta/Elev= 30
       0   963.7      29  961.71    48.4  959.88    58.1  958.76    67.8  956.89
    77.5  953.79   125.9  934.36   135.6  930.08   145.3  924.76   193.7  896.45
   242.1  867.48   271.2  849.58   280.8  844.17   358.3   804.5   377.5  796.26
     406  786.42   415.5  783.35     444  775.48   453.5  773.48     463  772.89
   472.5     773     482  773.79   558.1  781.64   567.7  783.12     587  788.37
   625.5  800.78   635.2  804.75   664.1  818.22   789.3  880.33   818.2  893.41
#Mann= 3 , 0 , 0
       0      .1       0   453.5    .045       0     482     .07       0
Bank Sta=453.5,482
XS Rating Curve= 0 ,0
Exp/Cntr=0.3,0.1

Type RM Length L Ch R = 1 ,28566.7 ,435.1,434.2,433.7
XS GIS Cut Line= 4
     1877831.229      637230.198     1878264.438      637357.181
     1878436.411      637406.316     1878780.931      637414.038
#Sta/Elev= 30
       0  901.68    39.3  898.51    68.7  894.77    88.3  890.74     108  885.56
   127.6  877.86   137.4  873.18   186.5  846.94   206.1  837.33   255.2  815.07
   274.8  807.98   304.2  800.92   333.7  795.11   412.2  784.36   441.6  779.07
   460.8  774.63   470.3   773.1   479.7     773   489.1   774.9   545.6   790.8
     555  794.89     602  819.68   620.9  828.38   639.9  835.14   764.3  875.16
   802.6  890.91   821.7  897.71   888.8  914.32   946.2   925.5   974.9  929.71
#Mann= 3 , 0 , 0
       0      .1       0   460.8    .045       0   489.1     .08       0
Bank Sta=460.8,489.1
XS Rating Curve= 0 ,0
Exp/Cntr=0.3,0.1