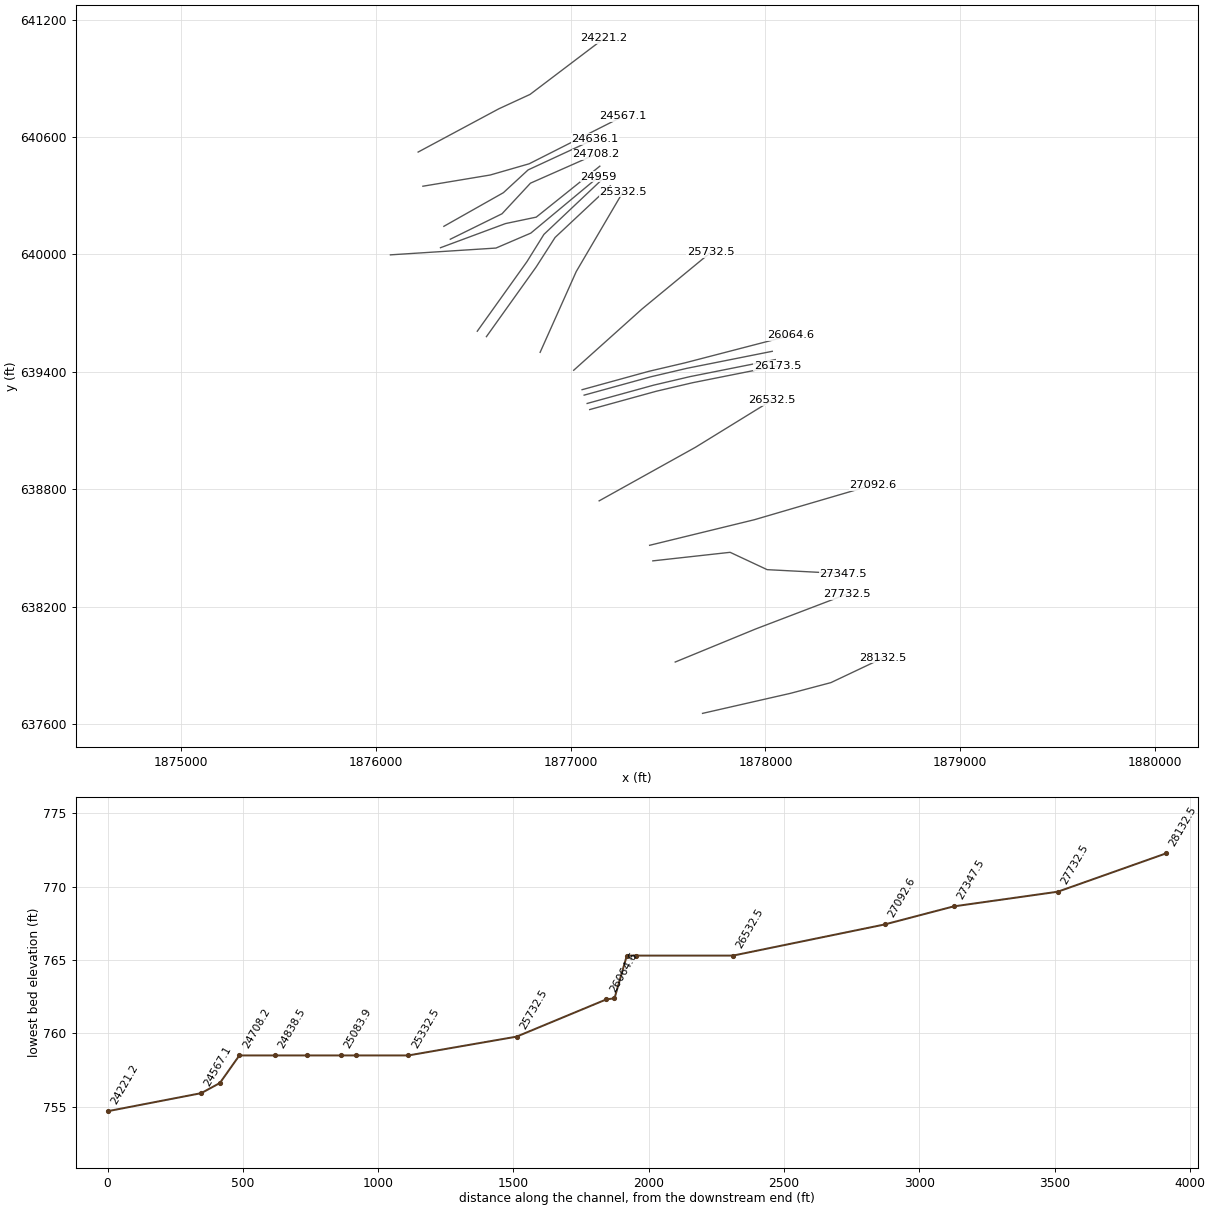
HEC-RAS study LFSpringCk.prj: LFSpringCk

--- LFSpringCk.g01 (geometry) --- (continued)

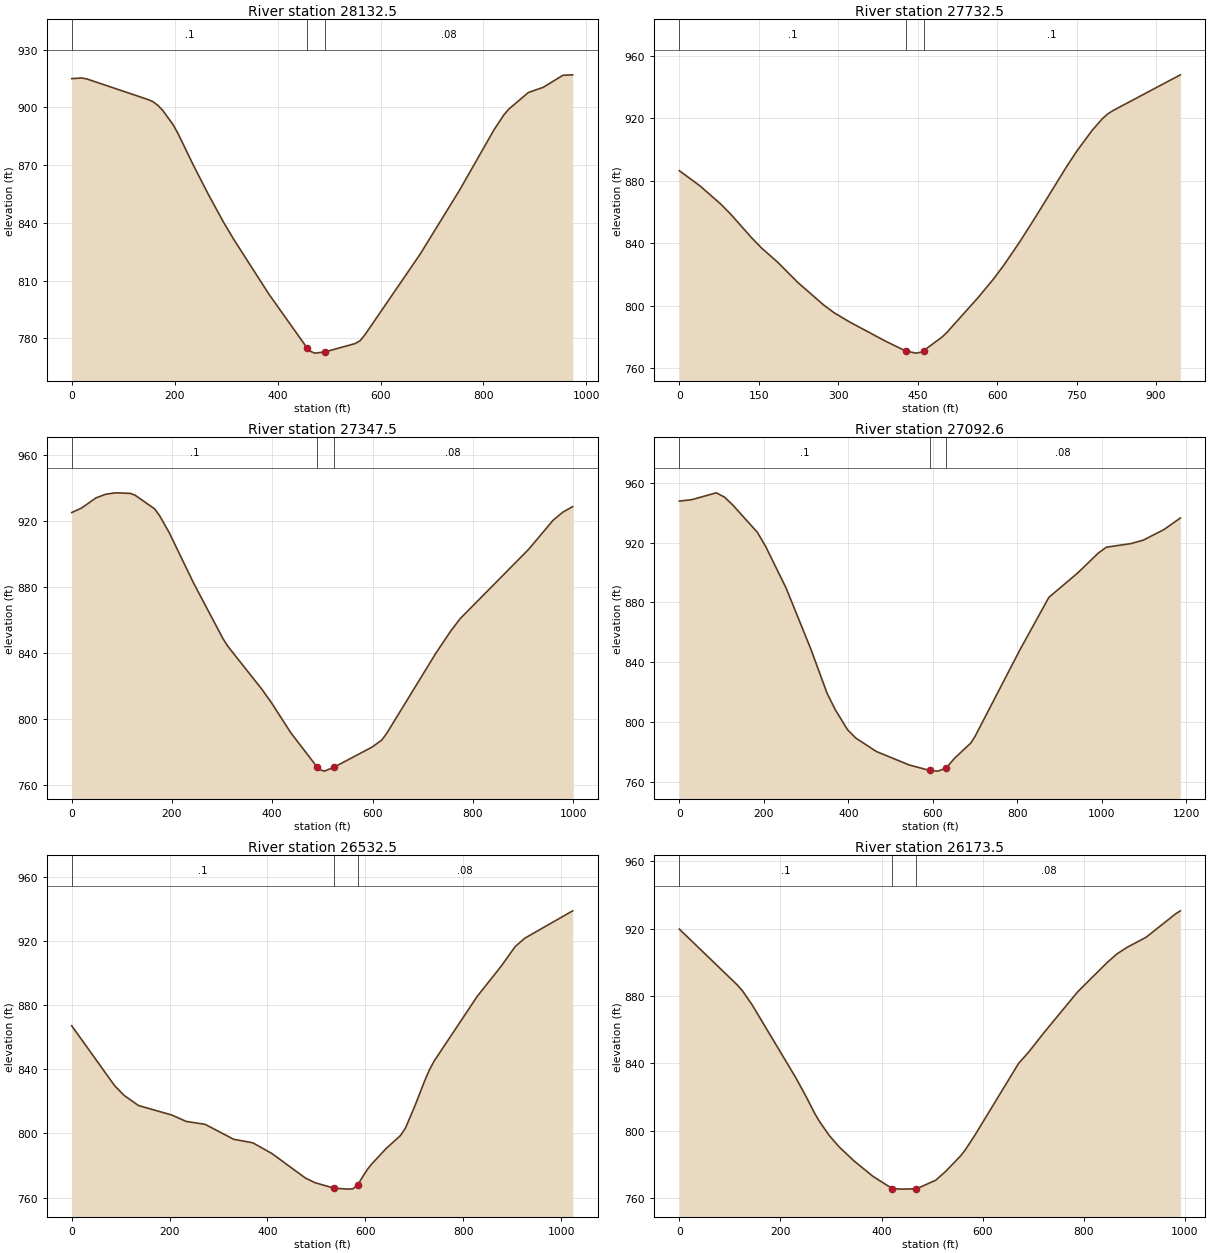
Type RM Length L Ch R = 1 ,28132.5 ,396.5,400,402
XS GIS Cut Line= 4
     1877677.266      637654.886     1878128.315      637757.288
     1878335.915      637812.039     1878603.848      637938.344
#Sta/Elev= 30
       0  914.92    19.7  915.22    29.5  914.73   147.6   904.1   157.5  902.99
   167.3  901.05   177.1  898.32   196.8  891.05   206.7   886.3   236.2  870.03
   265.7  854.63   295.2  840.19   314.9  831.34   383.8  802.66  457.97774.7232
   462.5  773.34   472.3  772.26   491.8  772.87   550.4   777.2   560.1  778.66
   569.9  781.87   677.2  823.76   753.7  856.99   820.6  888.35   839.7  896.08
   849.2  899.05   887.4  907.71   916.1  910.37   954.3  916.63   973.4  916.88
#Mann= 3 , 0 , 0
       0      .1       0  457.97    .045       0   491.8     .08       0
Bank Sta=457.97,491.8
XS Rating Curve= 0 ,0
Exp/Cntr=0.3,0.1

Type RM Length L Ch R = 1 ,27732.5 ,404,385,366.6
XS GIS Cut Line= 3
     1877537.088      637917.276     1877951.036      638086.641
     1878417.393      638263.841
#Sta/Elev= 30
       0   886.5    38.9  876.78    77.8  865.24    97.2  858.55   136.1  843.67
   155.6  836.84   184.7  828.17   223.6  814.94   272.2  800.56   291.7  795.64
   320.9  789.71   388.9  777.39   427.8  770.93   447.3  769.65     457  770.31
  461.57771.3033   496.2  779.98     506  783.21   564.6  805.43     594  817.46
   613.6  826.41   642.9     841   672.2  856.64   730.9  888.92   750.5  899.04
   779.8  912.46   799.4  920.03   809.2  922.95     819  925.04   946.1  947.92
#Mann= 3 , 0 , 0
       0      .1       0   427.8    .045       0  461.57      .1       0
Bank Sta=427.8,461.57
XS Rating Curve= 0 ,0
Exp/Cntr=0.3,0.1

Type RM Length L Ch R = 1 ,27347.5 ,238.5,254.9,270.9
XS GIS Cut Line= 4
     1877422.172      638434.169     1877818.691       638477.84
     1878008.795      638389.299     1878398.931      638369.046
#Sta/Elev= 30
       0  925.06    19.5  927.76    48.6  933.96    68.1  936.15    87.6  936.99
   116.8  936.67   126.5  935.54   165.4  927.28   175.1  923.29   194.6  912.86
   243.2  882.35   301.6  848.86   311.4  844.18   379.5  818.11   398.9  809.82
     437  791.86  489.91770.9792   494.2  769.62   503.8  768.65   522.8  770.94
   599.1  783.19   618.4  787.42   628.2  791.42   725.8  839.71   755.1  852.99
   774.7  860.83   911.4  902.81   960.2  920.39   979.8  925.33   999.3  928.64
#Mann= 3 , 0 , 0
       0      .1       0  489.91    .045       0   522.8     .08       0
Bank Sta=489.91,522.8
XS Rating Curve= 0 ,0
Exp/Cntr=0.3,0.1

Type RM Length L Ch R = 1 ,27092.6 ,561.2,560.1,564.4
XS GIS Cut Line= 3
     1877405.745      638513.729     1877943.691      638644.507
     1878550.462       638821.59
#Sta/Elev= 30
       0  947.64    29.1  948.58    87.4  953.16   106.8   950.3   126.3  945.05
   184.5  926.82     204  917.48   252.5  889.66   310.8  849.12   349.6  819.36
   369.1  808.34   398.2  794.98   417.6  789.49   466.2  780.51   543.9  771.54
   592.5  767.86     612  767.42   631.4  769.42   650.9  775.93   689.8  786.19
   699.5  790.46   806.4  848.61   874.5  883.39   942.6  899.64   991.2  912.89
  1010.7  916.88    1069  919.29  1098.2  921.62  1146.8  928.62  1185.7  936.37
#Mann= 3 , 0 , 0
       0      .1       0   592.5    .045       0   631.4     .08       0
Bank Sta=592.5,631.4
XS Rating Curve= 0 ,0
Exp/Cntr=0.3,0.1

Type RM Length L Ch R = 1 ,26532.5 ,358.5,359,352.7
XS GIS Cut Line= 3
     1877146.816      638740.861     1877640.791      639014.476
     1878032.006      639254.413
#Sta/Elev= 30
       0  867.12    87.6  829.81   107.1  823.72   136.3  817.41   204.5  811.49
   233.7  807.51   272.6  805.68     331  796.37     370  794.18   408.9  787.53
   477.1   772.3   496.5  769.38   535.5  765.92   564.7   765.3   574.5  765.46
   584.2  767.99   603.8  777.49   613.5  781.14   642.8  790.72   672.1  798.81
   681.9  803.35   701.4  817.33   720.9   832.6   730.7  839.52   740.4  845.06
   828.3  885.35   877.2  904.12   906.4  916.57     926  921.74  1023.6  938.75
#Mann= 3 , 0 , 0
       0      .1       0   535.5    .045       0   584.2     .08       0
Bank Sta=535.5,584.2
XS Rating Curve= 0 ,0
Exp/Cntr=0.3,0.1

Type RM Length L Ch R = 1 ,26173.5 ,33.6,33.5,33.6
XS GIS Cut Line= 4
     1877098.205      639207.224     1877440.219      639300.974
     1877625.983      639344.377     1878063.483      639431.182
#Sta/Elev= 30
       0  919.73     115  886.46   124.6  883.18   143.8  874.86     230  831.67
   249.2  821.16   268.4  809.96     278  805.14   297.1  796.97   316.3  790.36
     345  782.21   383.2  772.86   421.4  765.61   440.5   765.3   469.1  765.48
   507.2  770.58   526.3  775.64   555.1  784.59   564.8  788.18   584.2  797.05
   671.4  840.05   690.8  846.53   719.9  857.64   787.8  882.37     846  899.75
   865.4  904.88   884.8  908.72   923.6   914.9   981.7  928.74   991.4   930.6
#Mann= 3 , 0 , 0
       0      .1       0   421.4    .045       0   469.1     .08       0
Bank Sta=421.4,469.1
XS Rating Curve= 0 ,0
Exp/Cntr=0.3,0.1

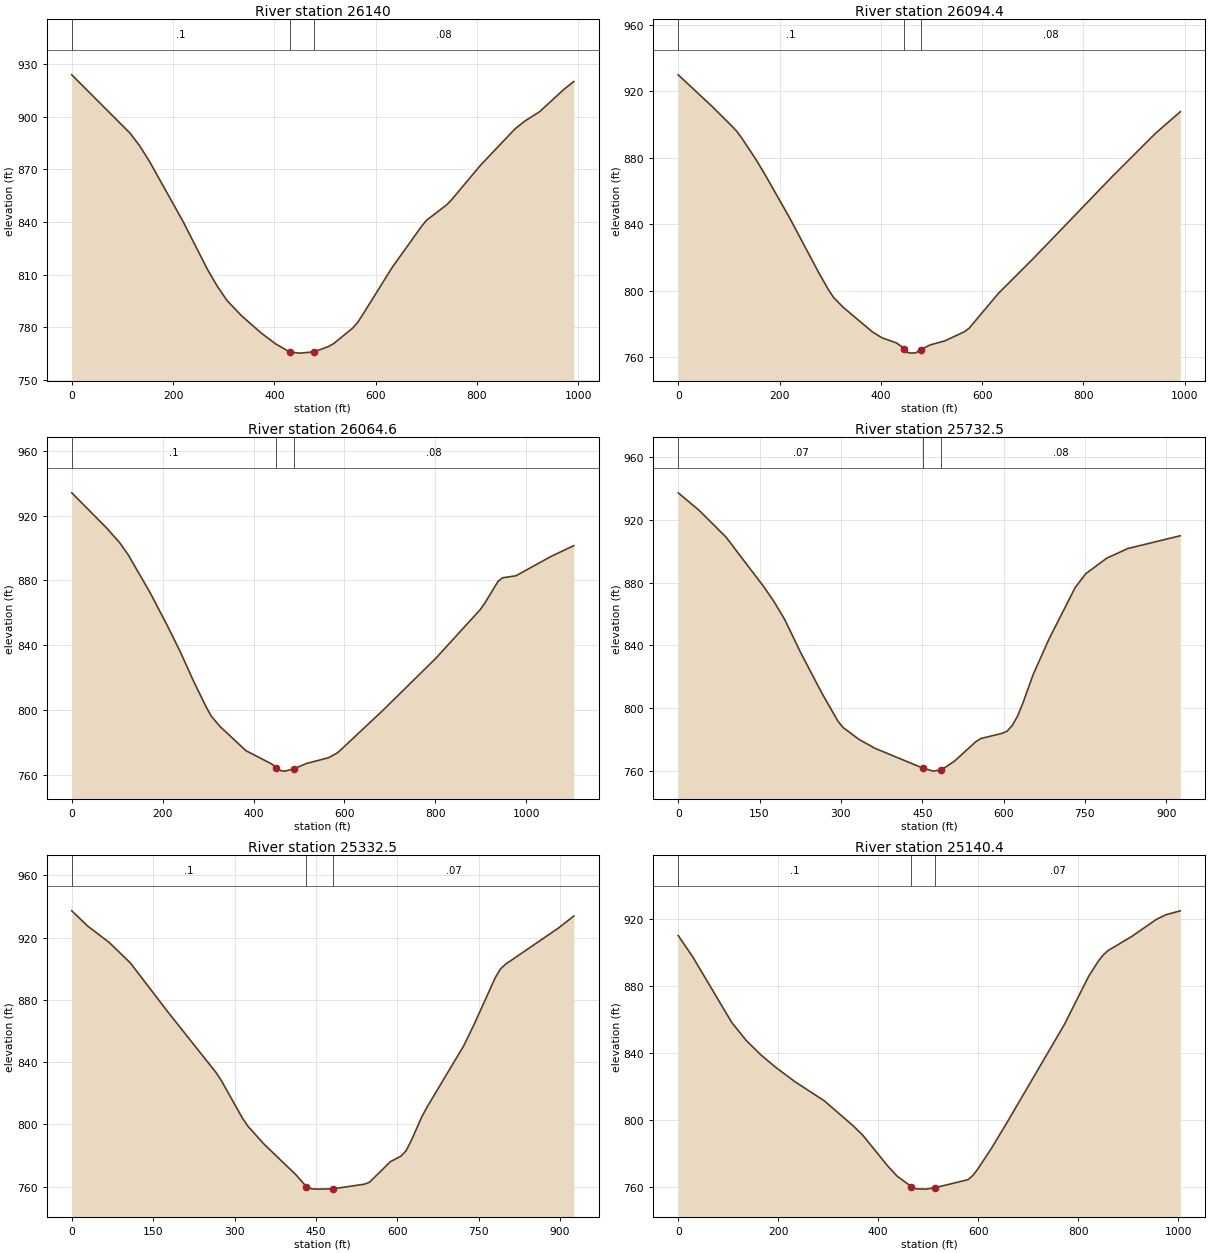
Type RM Length L Ch R = 1 ,26140   ,45.4,45.6,45.4
XS GIS Cut Line= 4
     1877085.184      639238.474     1877427.198      639332.224
     1877612.962      639375.627     1878050.462      639462.432
#Sta/Elev= 30
       0  923.96     115  890.74   134.2  883.41   153.4  874.65   220.4     840
   268.4  812.78   287.5  803.38   306.7  795.22   335.5  786.54   373.7  776.86
   402.3  770.62   430.9  765.88     450   765.3   478.6  766.04   507.2   769.1
   516.8  770.66   555.1  779.68   564.8  782.92   574.5  787.22   632.7  814.16
   690.8  837.62   700.5  841.03   739.3  849.63     749   852.4   807.2  872.44
   875.1   893.1   894.5  897.58   923.6  902.89     972  915.72   991.4  920.16
#Mann= 3 , 0 , 0
       0      .1       0   430.9    .045       0   478.6     .08       0
Bank Sta=430.9,478.6
XS Rating Curve= 0 ,0
Exp/Cntr=0.3,0.1

Type RM Length L Ch R = 1 ,26094.4 ,29.8,29.8,29.8
XS GIS Cut Line= 4
     1877069.776      639281.009      1877411.79      639374.759
     1877597.554      639418.162     1878035.054      639504.967
#Sta/Elev= 30
       0  929.96    67.1  910.86   105.4  899.27     115  896.16   124.6  892.27
   153.4  879.04   172.5  869.32   220.4  843.58     278  810.53   297.1  800.33
   306.7  795.95   325.9  789.94   383.2  775.23   402.3  771.62   430.9  768.54
   440.5  766.44  445.59764.5754     450  762.96   459.6  762.39   469.1  762.56
   478.6  764.46   497.7  767.37   526.3  769.75   564.8  775.22   574.5  777.42
   632.7  798.53   700.5  819.16   855.7  868.31   942.9  894.87   991.4  907.74
#Mann= 3 , 0 , 0
       0      .1       0  445.59    .045       0   478.6     .08       0
Bank Sta=445.59,478.6
XS Rating Curve= 0 ,0
Exp/Cntr=0.3,0.1

Type RM Length L Ch R = 1 ,26064.6 ,320.7,332.1,342.3
XS GIS Cut Line= 4
     1877059.143      639308.787     1877401.157      639402.537
      1877586.92      639445.939     1878128.587      639585.913
#Sta/Elev= 30
       0  934.04    76.7  912.35   105.4  903.28   124.6  895.62   172.5   872.4
   210.9  851.79   239.6  835.48   268.4  817.58   297.1  801.19   306.7  796.39
   325.9  789.96   383.2  774.95   440.5  766.66     450  764.53   459.6  762.61
   469.1  762.32   488.2  763.67   516.8  767.05     565  770.58   584.7  773.61
   594.5  776.11   682.8   799.3   800.6  831.79   898.7  861.93   908.6  865.83
     938  879.37   947.8   881.6   977.3  882.84  1055.8  894.96  1104.9  901.46
#Mann= 3 , 0 , 0
       0      .1       0     450    .045       0   488.2     .08       0
Bank Sta=450,488.2
XS Rating Curve= 0 ,0
Exp/Cntr=0.3,0.1

Type RM Length L Ch R = 1 ,25732.5 ,390.5,400,408
XS GIS Cut Line= 3
     1877016.161      639408.108     1877367.283      639721.629
     1877719.154      640010.402
#Sta/Elev= 30
       0  937.19    39.2  925.82    88.3  908.89   156.9  877.74   176.5  867.92
   196.1  856.62   225.6  835.44   264.8  809.56   294.2   791.8     304  787.57
   333.4     780   362.8  774.34   451.1  761.71   470.7  759.78  485.34760.5719
   509.5  766.16   548.2  778.36   557.9  780.55   596.6   783.8   606.3  785.22
     616  788.89   625.7  794.77   635.4  802.99   654.7  821.48   683.8  844.03
   732.2  876.91   751.6  885.65   790.3  895.54   829.1  901.68   925.9  909.84
#Mann= 3 , 0 , 0
       0     .07       0   451.1    .045       0  485.34     .08       0
Bank Sta=451.1,485.34
XS Rating Curve= 0 ,0
Exp/Cntr=0.3,0.1

Type RM Length L Ch R = 1 ,25332.5 ,195.4,192.2,191.1
XS GIS Cut Line= 3
     1876843.878      639499.714     1877029.099      639912.286
      1877269.37      640320.015
#Sta/Elev= 30
       0  937.18    29.5  927.36    68.8  916.94   108.1   903.7     177  872.34
   265.4   833.6   275.3  828.46   314.6  804.11   324.4  799.05   353.9  787.58
   412.9  767.82   432.6  760.06   442.4  758.66   452.2   758.5   481.2  758.69
   539.2  761.66   548.8  762.92   587.5  776.18   606.8  779.65   616.4  783.22
   626.1  789.87   645.4  805.04   655.1  811.28   722.7  850.63     742  864.53
   780.6  894.24   790.3  899.89   799.9  902.97   896.5  925.97   925.5  933.86
#Mann= 3 , 0 , 0
       0      .1       0   432.6    .045       0   481.2     .07       0
Bank Sta=432.6,481.2
XS Rating Curve= 0 ,0
Exp/Cntr=0.3,0.1

Type RM Length L Ch R = 1 ,25140.4 ,56.3,56.5,56.6
XS GIS Cut Line= 4
     1876568.257      639579.837     1876823.466       639935.74
     1876920.688      640086.781     1877203.674       640350.67
#Sta/Elev= 30
       0  909.82    29.2  897.04     107  857.99   136.2  847.16   165.4  838.62
   194.6  831.29   233.6  822.59     292  811.26   350.4   796.2   369.8  790.49
   418.5  772.53     438  766.22   466.3  760.06   475.8  758.68   494.7   758.5
   513.6  759.33   579.8  764.16   589.2  766.58   598.7   770.2   627.2  783.11
   656.3  797.48   772.4  856.66   820.7  885.26   840.1  894.41   849.7  898.02
   859.4  900.77   907.8  909.38   956.1   919.4   975.5  922.25  1004.5  924.59
#Mann= 3 , 0 , 0
       0      .1       0   466.3    .045       0   513.6     .07       0
Bank Sta=466.3,513.6
XS Rating Curve= 0 ,0
Exp/Cntr=0.3,0.1

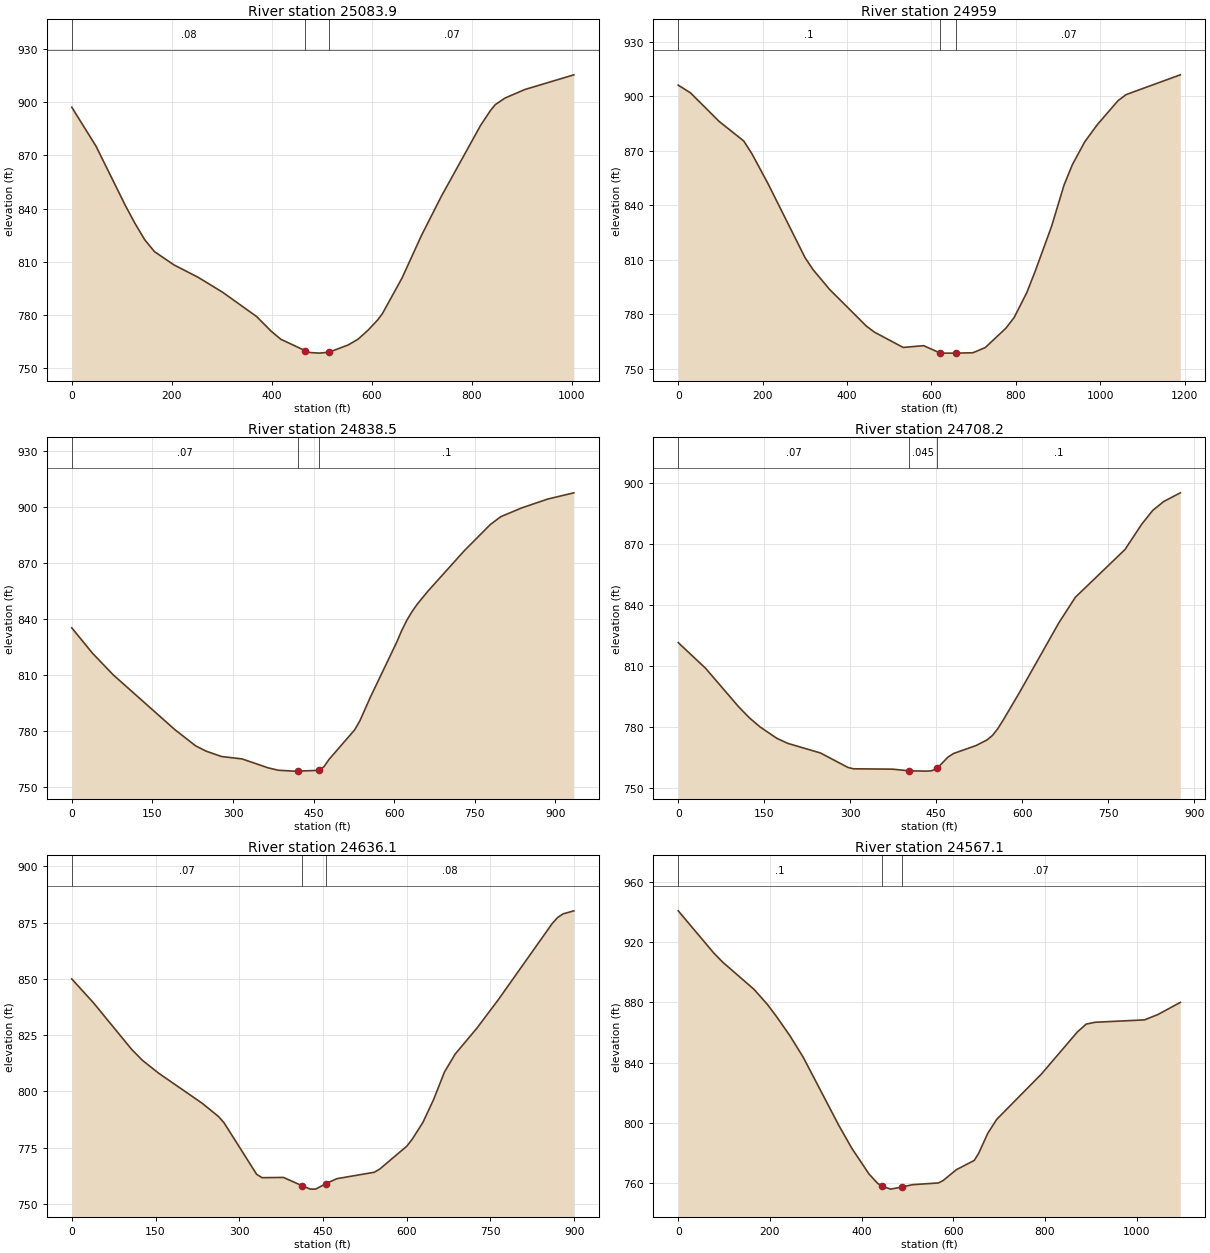
Type RM Length L Ch R = 1 ,25083.9 ,138.7,124.9,110.7
XS GIS Cut Line= 4
     1876521.382      639607.615     1876776.591      639963.517
     1876863.396      640102.406     1877156.799      640378.448
#Sta/Elev= 30
       0  897.21    48.7  875.14     107  841.91   126.5  831.66     146  822.45
   165.4  815.77   204.4  808.28     253  801.25   301.7  792.86   369.8  779.15
     399  770.86   418.5  766.27   466.8  759.93   476.5  758.83   495.8   758.5
     515  759.04   553.6  763.17   572.8  766.36   592.1  771.24   611.6  777.07
   621.4   780.7   660.7  800.79     700  825.03   739.3  846.86   817.9  886.91
   837.5  895.25   847.4  898.67     867  902.39   906.3  907.17  1004.6  915.48
#Mann= 3 , 0 , 0
       0     .08       0   466.8    .045       0     515     .07       0
Bank Sta=466.8,515
XS Rating Curve= 0 ,0
Exp/Cntr=0.3,0.1

Type RM Length L Ch R = 1 ,24959   ,123.9,120.5,115.7
XS GIS Cut Line= 4
     1876075.636      639997.806     1876617.302      640032.528
     1876796.122      640108.917     1877144.646      640397.545
#Sta/Elev= 30
       0  906.21    29.1  901.95    96.9  886.21   155.1  875.46   174.5  868.46
   213.2  851.71   300.5  811.14   319.8  804.43   358.6  793.63   445.8   773.4
   465.2  770.03   533.1  761.63   581.7  762.61   620.6  758.55   630.3   758.5
   659.4   758.5   698.3  758.71   727.5  761.55   776.6  772.26   796.3  778.23
   825.8  791.77   845.4  803.32   884.8  828.44   914.3  851.14     934  862.38
   963.5  875.02     993  884.39  1042.2  897.65  1061.9  901.04  1189.8  911.89
#Mann= 3 , 0 , 0
       0      .1       0   620.6    .045       0   659.4     .07       0
Bank Sta=620.6,659.4
XS Rating Curve= 0 ,0
Exp/Cntr=0.3,0.1

Type RM Length L Ch R = 1 ,24838.5 ,115.2,130.3,144.7
XS GIS Cut Line= 4
      1876332.58      640034.264     1876665.913      640157.528
       1876823.9      640190.514     1877150.288      640450.931
#Sta/Elev= 30
       0  835.22    38.4  821.69    76.8  810.15   192.1  780.65   230.5  772.04
   249.7  769.23   278.6  766.33     317  765.03   364.9   760.3   383.9  758.99
   412.4   758.5   421.8   758.5   459.8  758.92   469.3  760.86   478.8   764.8
   526.5  780.63   536.2  785.48   555.6  798.06   604.2  827.23   613.9  833.72
   623.6  839.33   633.3  843.96     643  847.94   662.4  854.74   730.4   876.5
     779  890.56   798.4  894.75   837.2  899.43   885.8  904.18   934.3  907.51
#Mann= 3 , 0 , 0
       0     .07       0   421.8    .045       0   459.8      .1       0
Bank Sta=421.8,459.8
XS Rating Curve= 0 ,0
Exp/Cntr=0.3,0.1

Type RM Length L Ch R = 1 ,24708.2 ,76.3,72.2,69.7
XS GIS Cut Line= 4
     1876382.927      640077.667     1876648.552      640207.875
     1876794.386      640364.125     1877129.455      640511.695
#Sta/Elev= 30
       0  821.58    47.7  808.98     105   790.2     124  784.69   143.1  780.11
   171.8  774.64   190.8  772.15   248.1   767.4   295.8  760.34   305.5  759.64
   373.5  759.47   402.7  758.65   431.8   758.5   441.6  758.64   451.3  759.83
   470.7  765.44   480.4  767.18   519.2  771.03   538.5  773.79   548.1  776.01
   557.7  779.48   567.4  783.82   596.3  797.63   663.7  831.22   692.6  843.82
   779.3  867.29   808.2  879.61   827.5  886.44   846.8  890.83   875.7  895.09
#Mann= 3 , 0 , 0
       0     .07       0   402.7    .045       0   451.3      .1       0
Bank Sta=402.7,451.3
XS Rating Curve= 0 ,0
Exp/Cntr=0.3,0.1

Type RM Length L Ch R = 1 ,24636.1 ,79.1,69,58.9
XS GIS Cut Line= 4
     1876349.941      640143.639     1876655.497      640315.514
     1876782.233      640431.833     1877124.247       640589.82
#Sta/Elev= 30
       0  849.95      39  839.32   107.1  818.72   126.6   813.8   155.8  808.07
   233.7  794.73   262.9  788.84   272.7   786.1   331.1  763.21   340.8   761.7
   379.2  761.81  412.24758.1664     427  756.65   436.6  756.62   455.7  759.09
   474.8  761.26   541.9  764.11   551.6  765.53   599.9  775.64   609.5  778.67
   628.9  786.22   648.2  796.45   667.5  808.59   686.8  816.61   725.5  828.04
   764.1  840.76   860.7  874.61   870.4  877.25     880  878.84   899.3  880.19
#Mann= 3 , 0 , 0
       0     .07       0  412.24    .045       0   455.7     .08       0
Bank Sta=412.24,455.7
XS Rating Curve= 0 ,0
Exp/Cntr=0.3,0.1

Type RM Length L Ch R = 1 ,24567.1 ,342.9,346,348.7
XS GIS Cut Line= 4
     1876242.302        640348.5     1876587.788      640405.792
     1876787.441      640463.083     1877267.476      640704.837
#Sta/Elev= 30
       0  940.92    77.8  912.79    97.3  906.72   165.4  888.72   194.6  878.67
     214  870.83   243.2  858.09   272.4  843.77   350.2  798.39   378.5  783.19
   416.3  765.96   435.2  759.74   444.6  757.88   463.5  755.93  487.31757.2762
   510.7  758.86   567.7  760.05   577.5  761.55   606.8  768.85   645.9  775.02
   655.6   779.8   675.2  792.95   694.7  802.26   792.4  832.45   870.6  860.33
   890.2  865.65   909.7  866.85  1017.2  868.43  1046.5  871.98  1095.4  880.06
#Mann= 3 , 0 , 0
       0      .1       0   444.6    .045       0  487.31     .07       0
Bank Sta=444.6,487.31
XS Rating Curve= 0 ,0
Exp/Cntr=0.3,0.1

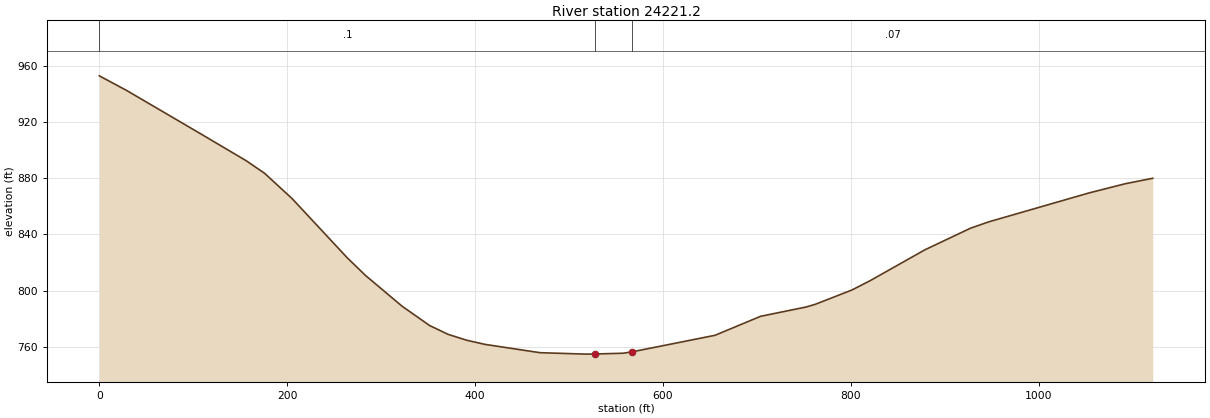
Type RM Length L Ch R = 1 ,24221.2 ,486.1,488.6,495.1
XS GIS Cut Line= 4
     1876217.877      640523.061     1876631.625      640743.899
     1876792.216      640817.684      1877171.99      641104.142
#Sta/Elev= 30
       0  952.96    29.3  942.44   107.5   911.8   156.3   892.5   175.9  883.54
   205.2  865.51   263.8  823.41   283.4  810.72   322.4  788.78   351.8     775
   371.3  768.78   390.8  764.65   410.4  761.66     469  755.73   518.1   754.7
   527.9   754.8   557.4  755.33   567.2  756.34   655.4  768.11     704  781.65
   752.5  788.28   762.2   790.2   801.1  800.36   820.5     807   878.7  828.96
   927.3  844.37   946.7  848.91  1053.5  869.52  1092.3  876.11  1121.4  879.98
#Mann= 3 , 0 , 0
       0      .1       0   527.9    .045       0   567.2     .07       0
Bank Sta=527.9,567.2
XS Rating Curve= 0 ,0
Exp/Cntr=0.3,0.1