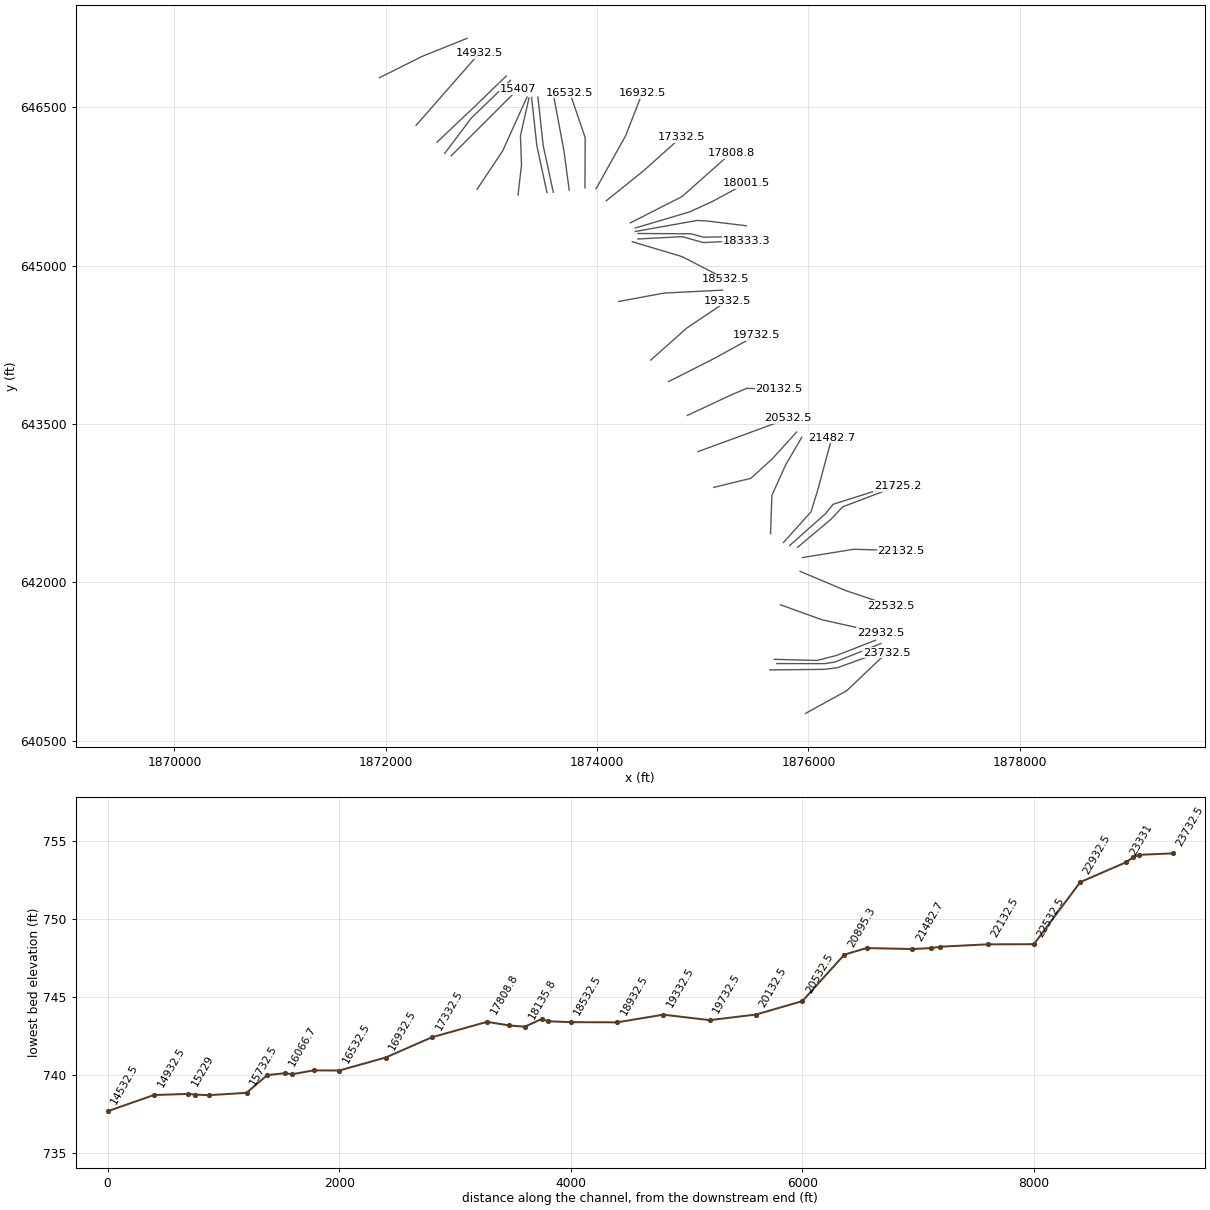
HEC-RAS study LFSpringCk.prj: LFSpringCk

--- LFSpringCk.g01 (geometry) --- (continued)

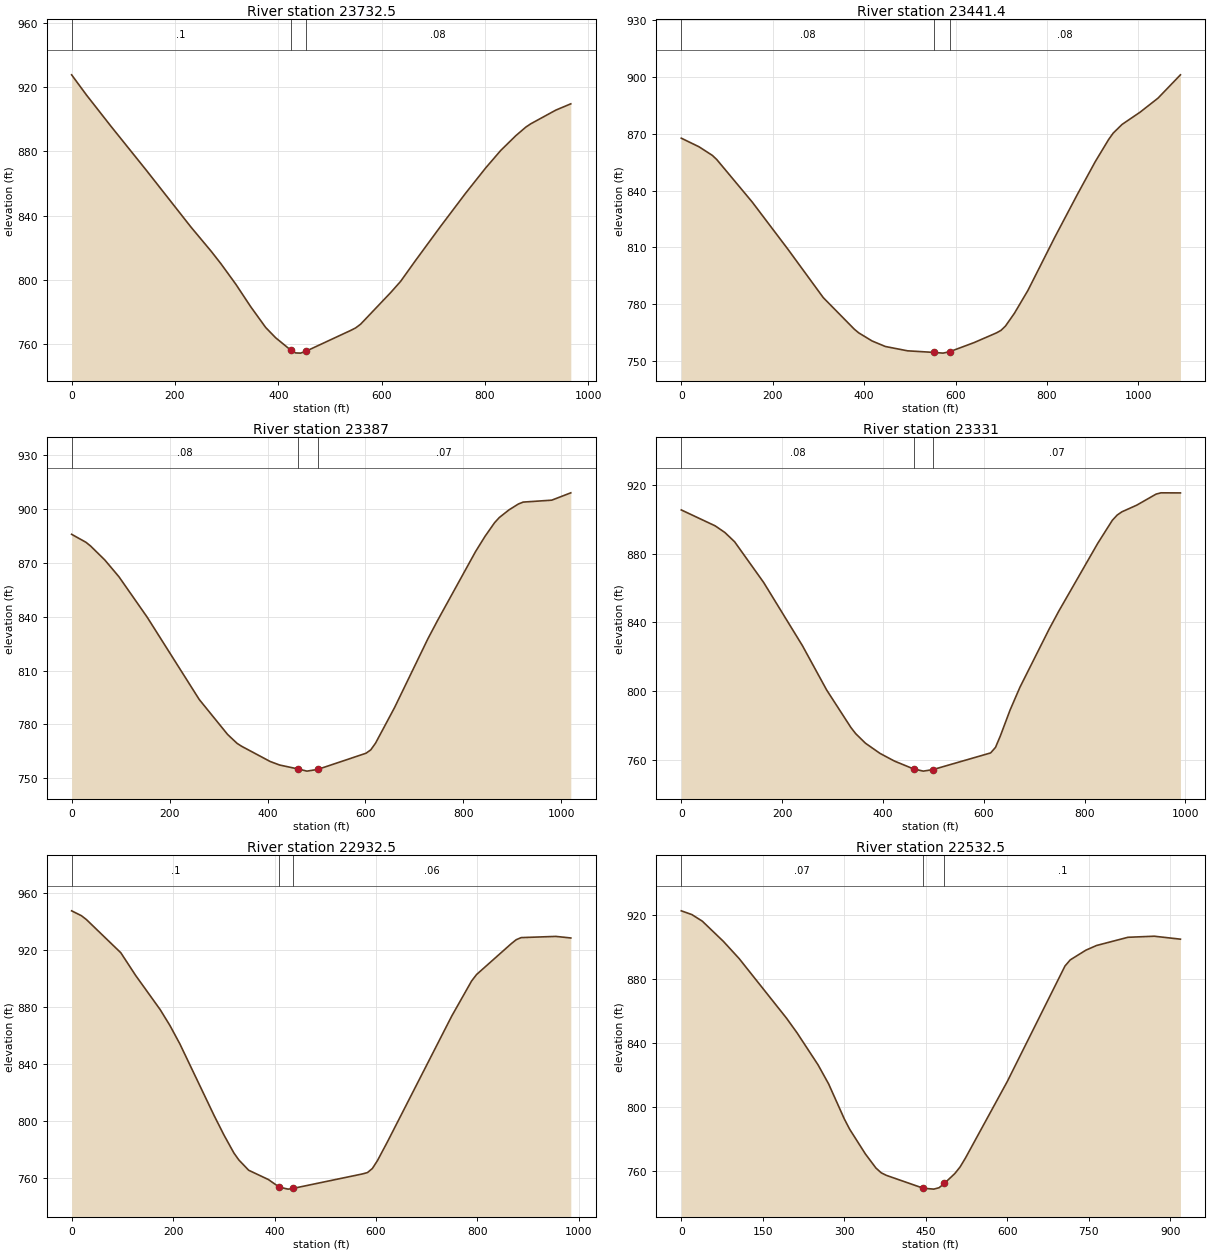
Type RM Length L Ch R = 1 ,23732.5 ,299.3,291.1,275.2
XS GIS Cut Line= 3
     1875973.509       640759.83     1876361.438      640973.793
      1876740.68      641333.972
#Sta/Elev= 30
       0  927.81    28.9  915.15      77  895.38   144.5  868.31   231.1  832.79
   269.7   817.9   288.9  810.01   317.8  797.18   346.7  783.12   375.6   770.2
   394.9  763.79   423.8  756.18   433.4  754.36     443  754.23   452.7   755.3
   539.9  768.36   549.6  769.95   559.2  772.27   617.4  791.99   636.7     799
   665.8  812.12   714.2  833.38   762.6  854.03   801.4  869.79   830.4  880.64
   859.5  889.82   878.9  895.18   888.6  897.28     937   905.8     966  909.72
#Mann= 3 , 0 , 0
       0      .1       0   423.8    .045       0   452.7     .08       0
Bank Sta=423.8,452.7
XS Rating Curve= 0 ,0
Exp/Cntr=0.3,0.1

Type RM Length L Ch R = 1 ,23441.4 ,53.7,54.4,55.9
XS GIS Cut Line= 4
     1875635.061      641171.417     1876149.384      641176.625
     1876274.384       641192.25       1876698.9      641345.896
#Sta/Elev= 30
       0  867.65    38.8   863.1    67.9  858.57    77.6  856.37   155.3  833.88
   232.9  809.12   310.6  783.44   378.5  766.77   388.2  764.83   417.3  760.56
   446.4  757.64   494.9  755.36   552.9  754.51   572.5  754.14   587.2754.9039
   640.3  759.69   689.4  764.83   699.2  766.14     709  768.41   728.6  775.17
   758.1  787.22     817  815.36     866   837.8   905.3  855.19   934.8  866.98
   944.6   870.3   964.2  874.93  1003.5  881.37  1042.7  888.79  1091.8   901.1
#Mann= 3 , 0 , 0
       0     .08       0   552.9    .045       0   587.2     .08       0
Bank Sta=552.9,587.2
XS Rating Curve= 0 ,0
Exp/Cntr=0.3,0.1

Type RM Length L Ch R = 1 ,23387   ,53.2,56,58
XS GIS Cut Line= 4
     1875701.468      641231.313     1876155.027      641230.879
     1876252.683      641246.504     1876685.464      641421.256
#Sta/Elev= 30
       0  885.92      29  881.52    38.6  879.43    67.6  871.67    96.5  862.32
   154.4   839.7   260.6  793.88   318.5   774.4   337.8  769.45   347.4  767.78
   405.3  759.36   424.6  757.39   462.6  755.16   480.5  753.98  502.56754.9406
   601.1  763.95   610.8  765.84   620.5  769.56   659.4  789.41   727.5  827.76
   746.9  837.78   824.7  876.29   844.2  884.84   863.6   892.4   873.3  895.28
   892.8  899.49   912.2  902.81     922  903.87   980.3  904.94  1019.2  909.03
#Mann= 3 , 0 , 0
       0     .08       0   462.6    .045       0  502.56     .07       0
Bank Sta=462.6,502.56
XS Rating Curve= 0 ,0
Exp/Cntr=0.3,0.1

Type RM Length L Ch R = 1 ,23331   ,411.4,398.4,389.6
XS GIS Cut Line= 4
     1875677.596      641271.677     1876081.242      641260.826
     1876265.704       641308.57     1876634.627      641451.799
#Sta/Elev= 30
       0  905.31    67.3  896.06    86.5  892.21   105.8  886.83   163.4   863.2
   240.4  826.46   288.4  800.75   336.5  778.98   346.1  775.38   365.3  769.88
   394.2  763.96   422.8  759.51     461  754.92     480  753.67   499.1  754.55
   613.6  764.24   623.3  767.47   632.9  774.13   652.2  789.16   671.6   802.3
   729.5  836.05   748.8  846.55     826   885.9     855   899.3   864.6  902.34
   874.2  904.25   903.2  908.05   941.8   914.5   951.5  915.24   990.1  915.19
#Mann= 3 , 0 , 0
       0     .08       0     461    .045       0   499.1     .07       0
Bank Sta=461,499.1
XS Rating Curve= 0 ,0
Exp/Cntr=0.3,0.1

Type RM Length L Ch R = 1 ,22932.5 ,401.7,400,395.7
XS GIS Cut Line= 3
     1875735.322       641788.17     1876127.485      641646.347
     1876681.114      641523.176
#Sta/Elev= 30
       0  947.48    19.4  944.04    29.1  941.37      97  918.09   126.1  902.25
   174.6  878.23     194  866.99   213.4  854.21   281.2  803.78   300.6  790.16
     320   777.7   329.7  772.84   349.1  765.62   387.9  759.12   409.5  753.77
   426.8  752.39   436.6   752.9   573.5  763.05   583.3  763.99     593  766.87
   602.8  772.27   622.4  785.36   749.5  873.74   788.6  898.29   798.4  902.83
   866.8  924.45   876.6  927.24   886.4  928.71   954.8  929.55   984.2  928.45
#Mann= 3 , 0 , 0
       0      .1       0   409.5    .045       0   436.6     .06       0
Bank Sta=409.5,436.6
XS Rating Curve= 0 ,0
Exp/Cntr=0.3,0.1

Type RM Length L Ch R = 1 ,22532.5 ,386.9,400,406.4
XS GIS Cut Line= 3
     1875921.703      642104.345     1876350.004      641923.723
     1876780.186      641779.143
#Sta/Elev= 30
       0  922.47    19.4  920.14    38.7     916    77.5  903.37   106.5  892.61
   193.7  855.32     213   846.2   251.8  826.11   271.2   814.2   300.2  792.22
   309.9  785.88   338.9  770.38   358.3  761.58     368  758.62   377.7  756.99
   445.5  748.96   464.8  748.41   474.5   749.3   484.1  751.98   503.4  758.13
   513.1  762.26   522.8  767.73     600  815.73   706.2  887.96   715.9   891.8
   744.8  897.89   764.2  900.78   822.1  905.92   870.4  906.59   918.7  904.74
#Mann= 3 , 0 , 0
       0     .07       0   445.5    .045       0   484.1      .1       0
Bank Sta=445.5,484.1
XS Rating Curve= 0 ,0
Exp/Cntr=0.3,0.1

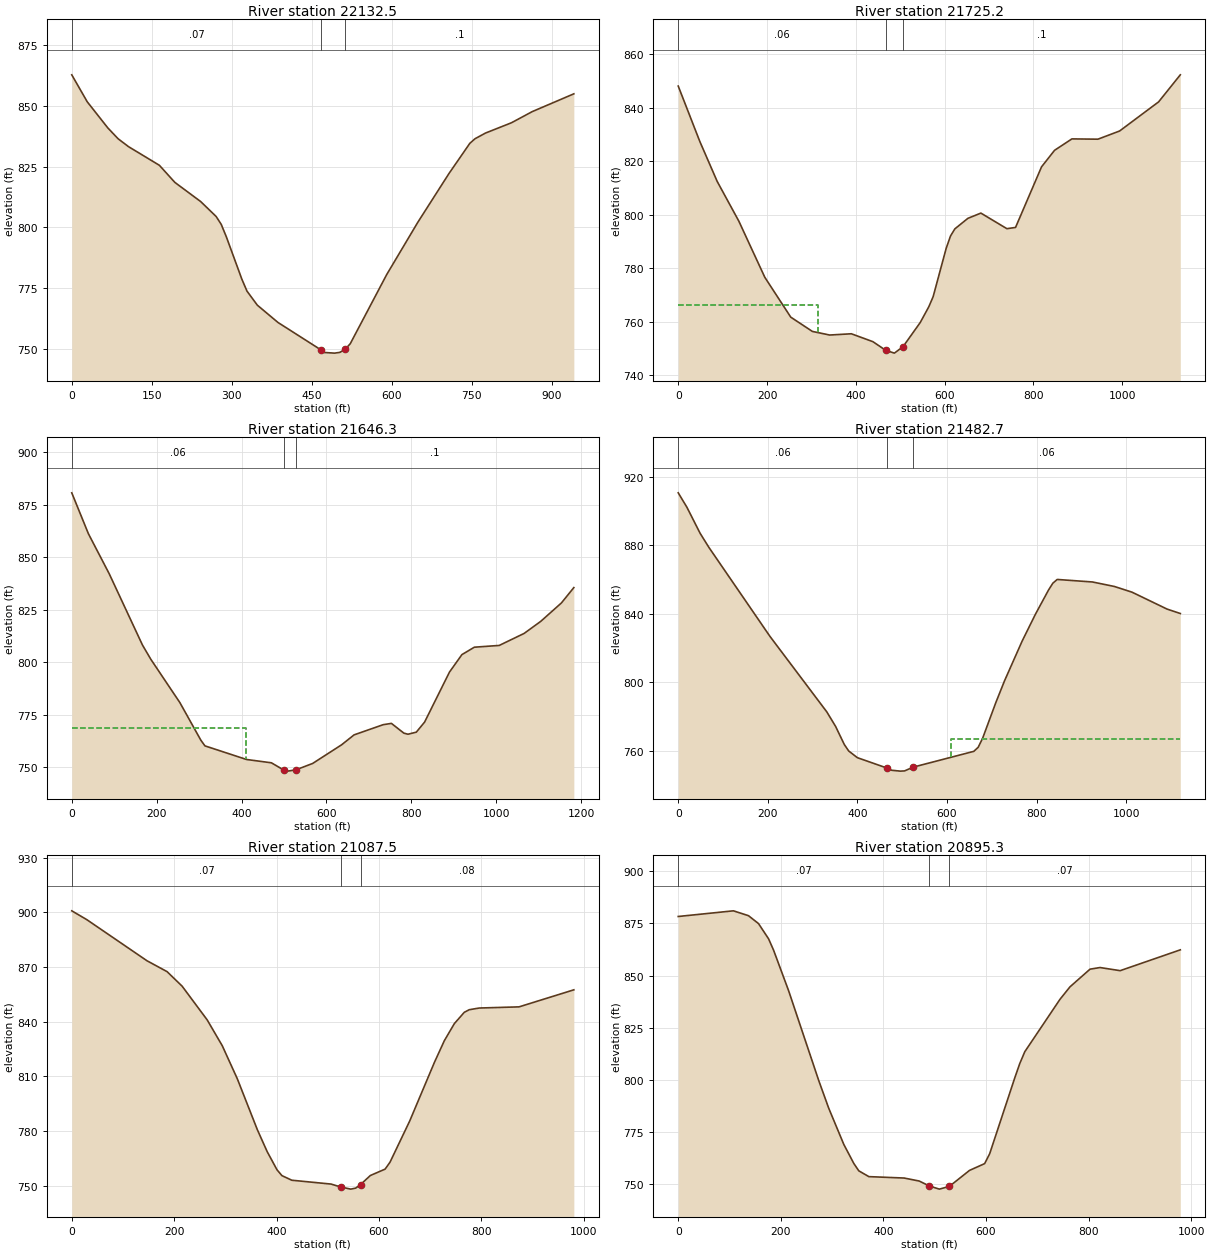
Type RM Length L Ch R = 1 ,22132.5 ,392.2,407.3,426.1
XS GIS Cut Line= 3
     1875943.264      642235.173     1876429.583      642313.961
     1876877.744      642300.799
#Sta/Elev= 30
       0  862.66      29  851.59    67.6  840.86    86.9   836.4   106.3  833.18
   164.2  825.52   193.2   818.5   241.5  810.65   270.5  804.52   280.1  801.28
   289.8   796.1   318.8  778.75   328.4  773.86   347.8  768.09   386.4     761
  467.13749.7141   473.3  748.66   492.7   748.4   502.4  748.71   512.2  749.94
   521.9  752.24   590.1  780.59   648.6  802.13   707.1  822.18   746.1  834.54
   755.8  836.42   775.3  838.74     824  842.97     863  847.55     941  854.86
#Mann= 3 , 0 , 0
       0     .07       0  467.13    .045       0   512.2      .1       0
Bank Sta=467.13,512.2
XS Rating Curve= 0 ,0
Exp/Cntr=0.3,0.1

Type RM Length L Ch R = 1 ,21725.2 ,77.4,79,80.6
XS GIS Cut Line= 4
     1875897.488      642332.561     1876211.016      642595.896
     1876324.297      642715.688     1876844.697      642913.604
#Sta/Elev= 30
       0  848.16    48.7  827.41    87.7  812.51   136.5  797.64     195  776.64
   253.5  761.71   302.2  756.37   341.2  755.02     390  755.49   438.5  752.54
   467.6  749.29     487  748.25   506.4  750.66   545.2   759.7   564.6  765.63
   574.3  769.38   603.6  787.44   613.4  792.07   623.2  794.74   652.5  798.67
   681.8  800.64   740.4  794.81   759.9  795.27   818.5  817.95   847.8  824.13
   886.9   828.4   945.5  828.29   994.3  831.35  1082.2  842.25  1131.1  852.37
#Mann= 3 , 0 , 0
       0     .06       0   467.6    .045       0   506.4      .1       0
#XS Ineff= 2 , 0
          315.05  766.18
Permanent Ineff=
       F       F
Bank Sta=467.6,506.4
XS Rating Curve= 0 ,0
Exp/Cntr=0.3,0.1

Type RM Length L Ch R = 1 ,21646.3 ,155,163.6,172.1
XS GIS Cut Line= 4
     1875823.429      642350.236     1876160.669      642649.715
     1876234.454      642739.993     1876821.259      642925.757
#Sta/Elev= 30
       0  880.59    39.2  861.13    88.2   842.1   166.7  808.12   186.3  801.38
   254.9  780.72     304  762.94   313.8  760.18   411.8   753.7   470.4  752.12
   499.6  748.68   509.3  748.16   528.8  748.82   567.6  751.81     636  760.71
   665.3  765.42   733.7  770.25   753.2  770.88   782.6  766.23   792.3  765.72
   811.9  766.71   831.4  771.49     890  795.27   919.3  803.59   948.6  807.13
  1007.3  807.97  1065.9  813.68    1105  819.41  1153.8  828.19  1183.1   835.5
#Mann= 3 , 0 , 0
       0     .06       0   499.6    .045       0   528.8      .1       0
#XS Ineff= 2 , 0
          411.37  768.63
Permanent Ineff=
       F       F
Bank Sta=499.6,528.8
XS Rating Curve= 0 ,0
Exp/Cntr=0.3,0.1

Type RM Length L Ch R = 1 ,21482.7 ,397.9,395.1,392.3
XS GIS Cut Line= 4
     1875763.968       642377.58     1876024.384      642668.379
     1876089.488      642878.882     1876221.867      643371.504
#Sta/Elev= 30
       0  910.69    19.5   902.2    48.8  887.08    68.3  878.87   204.9  826.77
   331.8  782.66   351.3  774.22   370.8  763.62   380.6  759.85   399.9  755.96
     467   749.8   476.6   748.6   495.7   748.1   505.3  748.23   524.5  750.43
   659.8  759.65   669.6  762.03   679.4  767.24   708.8  788.02   728.4  800.86
   767.6  824.01   797.1  839.62   826.5  853.84   836.3  857.91   846.1  860.08
   924.6  858.61   973.7  855.98  1012.9  852.66  1091.4  842.75  1120.8  840.19
#Mann= 3 , 0 , 0
       0     .06       0     467    .045       0   524.5     .06       0
#XS Ineff= 2 , 0
                          608.03          766.91
Permanent Ineff=
       F       F
Bank Sta=467,524.5
XS Rating Curve= 0 ,0
Exp/Cntr=0.3,0.1

Type RM Length L Ch R = 1 ,21087.5 ,201.5,192.2,183
XS GIS Cut Line= 4
     1875641.572      642462.215     1875654.593      642824.629
     1875784.801      643113.257     1875936.711      643373.674
#Sta/Elev= 30
       0  900.76    29.4  895.92     147  873.37   186.2  867.41   215.6  859.44
   264.6  840.93     294  826.79   323.4  808.67   362.6   780.7   381.8  768.68
     401  758.73   410.6  755.56   429.8  753.04   506.6  750.93   525.8   749.3
     545  748.16   554.6  748.71   564.1  750.65   583.3  755.63   612.1  759.13
   621.7  762.93   660.1  785.47   708.5   817.7   727.9   829.6   747.4  838.92
   766.8  845.12   776.5  846.54     796  847.46   873.8   848.1   980.8  857.44
#Mann= 3 , 0 , 0
       0     .07       0   525.8    .045       0   564.1     .08       0
Bank Sta=525.8,564.1
XS Rating Curve= 0 ,0
Exp/Cntr=0.3,0.1

Type RM Length L Ch R = 1 ,20895.3 ,371.5,362.8,354.1
XS GIS Cut Line= 4
     1875103.811      642899.715     1875455.374      642985.653
     1875658.499      643170.549     1875888.381      643424.232
#Sta/Elev= 30
       0  878.27   107.6  880.98   136.9  878.66   156.5  874.88   176.1   867.6
   185.8  862.21   215.2  842.74   273.9  799.76   293.4  786.49   322.8  769.16
   342.4     760   352.1  756.49   371.7  753.72   440.4  753.05   469.8  751.62
   489.4  749.26   509.1  747.74   528.7  749.06   567.9   756.7   597.4  759.95
   607.2  764.67   656.2  801.04   665.9  807.86   675.7  813.54   744.2  838.58
   763.8  844.59   802.9  853.05   822.4  853.83   861.6  852.33   978.9   862.3
#Mann= 3 , 0 , 0
       0     .07       0   489.4    .045       0   528.7     .07       0
Bank Sta=489.4,528.7
XS Rating Curve= 0 ,0
Exp/Cntr=0.3,0.1

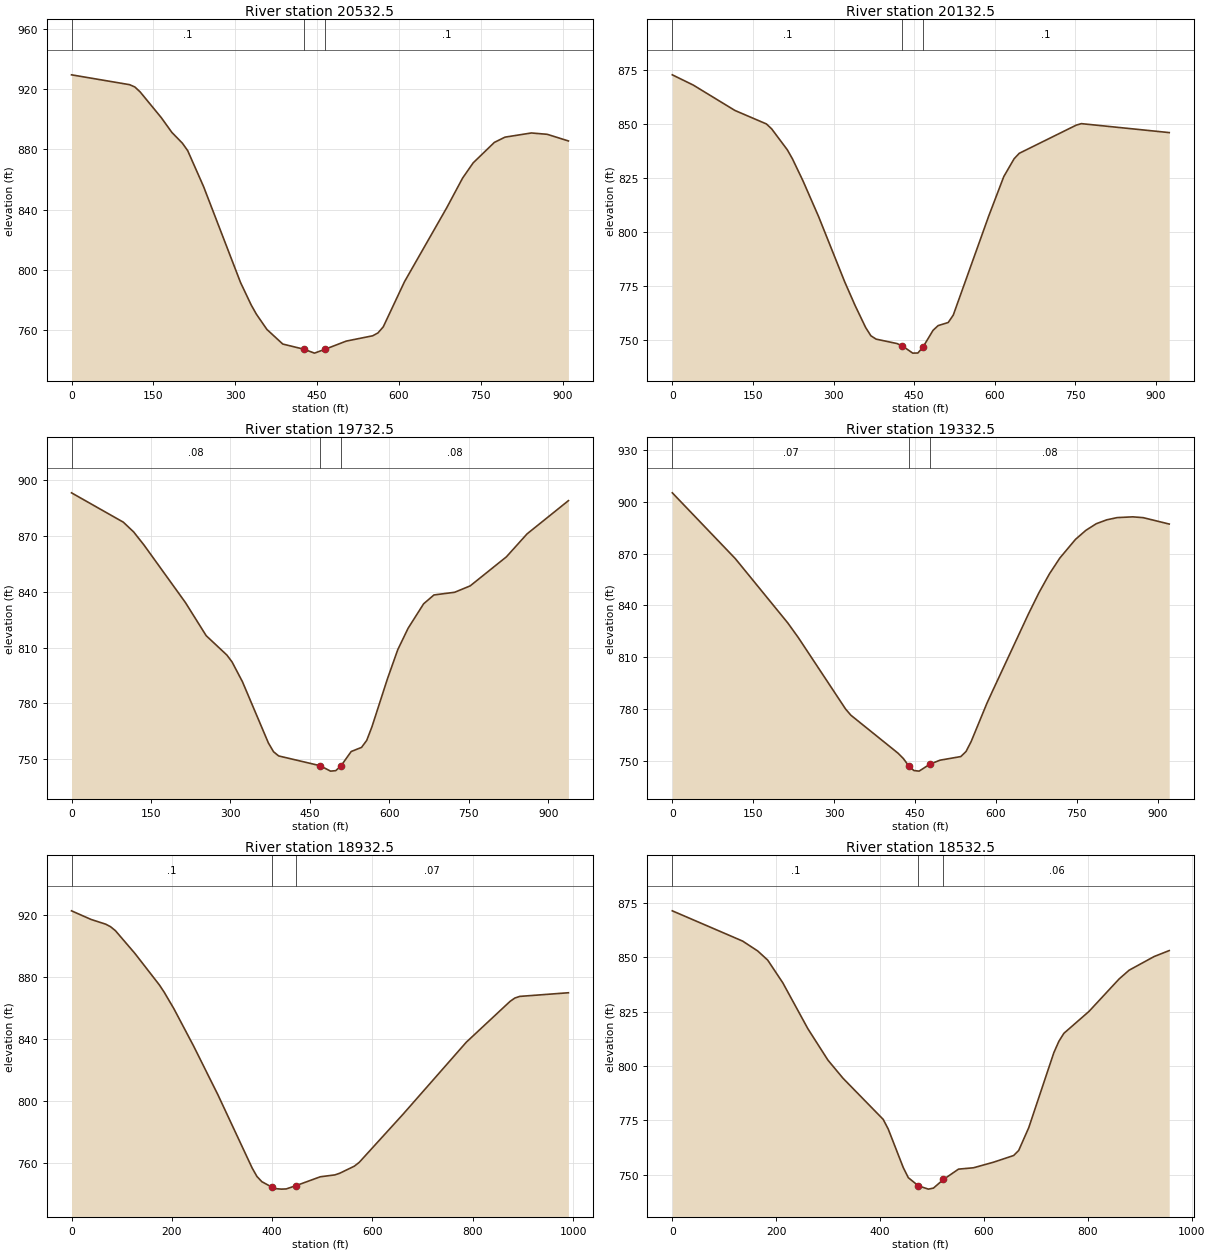
Type RM Length L Ch R = 1 ,20532.5 ,398,400,401
XS GIS Cut Line= 3
     1874955.277      643238.832     1875382.575      643394.853
     1875809.855      643553.019
#Sta/Elev= 30
       0  929.44   106.5   922.9   116.1  921.37   125.8  918.09   164.5  901.02
   183.9  891.23   203.2  884.05   212.9  879.12     242  855.27   309.7  791.63
   329.1  776.81   338.8  770.58   358.1  760.45   387.1  750.78   425.9  747.35
   445.2  744.76   464.6  747.33   503.4  752.74   551.8  756.26   561.5  758.16
   571.2  762.19     610  792.07   687.6  841.29   716.6  860.93     736  871.04
   774.8   884.6   794.2  888.08   842.6  890.86   871.7  889.96   910.5  885.56
#Mann= 3 , 0 , 0
       0      .1       0   425.9    .045       0   464.6      .1       0
Bank Sta=425.9,464.6
XS Rating Curve= 0 ,0
Exp/Cntr=0.3,0.1

Type RM Length L Ch R = 1 ,20132.5 ,399.2,400,402
XS GIS Cut Line= 4
     1874854.359       643581.08     1875268.265      643775.128
     1875415.362      643837.369     1875723.169      643829.837
#Sta/Elev= 30
       0  872.76    38.9  868.03   116.7  856.24   175.1  850.02   184.8  847.77
     214  838.06   223.7  833.81   243.2  823.67   272.3   807.1     321  776.82
   340.4  765.84   359.9  755.73   369.6  751.93   379.3  750.38   418.2  748.33
     428  747.26   447.4   743.9   457.1  743.96   466.5   746.7   485.3  754.47
   494.7  756.64   513.5  758.08   522.9  761.52   588.7  807.26   616.9  825.64
   636.1  833.89   645.7  836.42   751.6  849.45   761.2  850.16   924.8  846.01
#Mann= 3 , 0 , 0
       0      .1       0     428    .045       0   466.5      .1       0
Bank Sta=428,466.5
XS Rating Curve= 0 ,0
Exp/Cntr=0.3,0.1

Type RM Length L Ch R = 1 ,19732.5 ,393.9,400,401.4
XS GIS Cut Line= 3
     1874677.355      643901.835      1875113.24      644123.054
      1875506.68       644339.47
#Sta/Elev= 30
       0  893.32    97.8  877.52   117.3  872.27   136.9  865.19   215.1  834.22
   254.2  816.42   293.3  805.99   303.1  802.25   322.6  791.65   371.5  758.74
   381.3  753.96     391  751.71   469.3  746.45   488.8  743.54   498.6  743.79
   508.3  746.26   527.8  754.09   547.4  756.32   557.1  760.08   566.9  767.32
   596.2  793.19   615.7  808.89   635.2  820.42   664.5  833.59     684  838.35
   723.1   839.8   752.4  843.24   820.7  858.86   859.8  871.24   937.8  889.11
#Mann= 3 , 0 , 0
       0     .08       0   469.3    .045       0   508.3     .08       0
Bank Sta=469.3,508.3
XS Rating Curve= 0 ,0
Exp/Cntr=0.3,0.1

Type RM Length L Ch R = 1 ,19332.5 ,412.4,400,388.1
XS GIS Cut Line= 3
     1874508.116      644105.326     1874850.009      644409.761
     1875235.336      644668.175
#Sta/Elev= 30
       0  905.16   116.9  867.02   214.3  829.72   233.8  821.24   321.4  779.88
   331.2   776.3   418.8  754.26   428.6  751.17   438.3  747.04     448  744.24
   457.8  743.89   477.1  747.79   496.4  750.22   535.1  752.33   544.8  755.25
   554.4   761.1   583.4  783.09   593.1  789.72   660.8  835.12   680.1   847.3
   699.4  858.15   718.8  867.37   747.8  878.18   767.1  883.43   786.4  887.26
   805.8  889.51   825.1   890.8   854.1  891.24   873.4  890.77   921.7  887.07
#Mann= 3 , 0 , 0
       0     .07       0   438.3    .045       0   477.1     .08       0
Bank Sta=438.3,477.1
XS Rating Curve= 0 ,0
Exp/Cntr=0.3,0.1

Type RM Length L Ch R = 1 ,18932.5 ,410.1,400,388.1
XS GIS Cut Line= 3
     1874204.756      644660.334     1874635.159      644740.057
     1875187.366      644767.609
#Sta/Elev= 30
       0  922.63    38.9  917.09    68.1  914.04    77.8   912.4    87.5  909.86
   126.4  895.19   175.1  874.93   184.8  870.21   204.3  859.47   243.2  835.67
   291.8   804.2   359.9  757.14   369.6  751.58   379.4  748.19   398.8  744.79
   408.5  743.67   418.3   743.4     428  743.53   447.4  745.62   495.9  751.35
     525  752.56   534.7  753.63   563.8  758.18   573.5  760.62   660.8   791.6
   786.9  837.99   874.2   864.3   883.9  866.49   893.6  867.52   990.6  869.87
#Mann= 3 , 0 , 0
       0      .1       0   398.8    .045       0   447.4     .07       0
Bank Sta=398.8,447.4
XS Rating Curve= 0 ,0
Exp/Cntr=0.3,0.1

Type RM Length L Ch R = 1 ,18532.5 ,198.7,199.2,203.2
XS GIS Cut Line= 3
     1874332.728      645226.491     1874805.037       645084.84
     1875217.164      644872.202
#Sta/Elev= 30
       0  871.43   135.4  857.51   164.4  852.97   183.7  848.76   212.7  838.34
     261  817.21   299.7  802.74   328.7  794.41   406.1  775.48   415.8  771.02
   444.8  753.27   454.4  748.69   473.8  744.92   493.1  743.41   502.8  743.88
   522.1  747.86   551.1  752.61     580  753.23   618.7  755.81   657.3  758.88
     667  761.21   686.3  771.68   734.6  806.16   744.3   811.4     754  815.09
   802.3  825.16   860.2  840.06   879.6  844.12   927.9  850.42   956.8  853.15
#Mann= 3 , 0 , 0
       0      .1       0   473.8    .045       0   522.1     .06       0
Bank Sta=473.8,522.1
XS Rating Curve= 0 ,0
Exp/Cntr=0.3,0.1

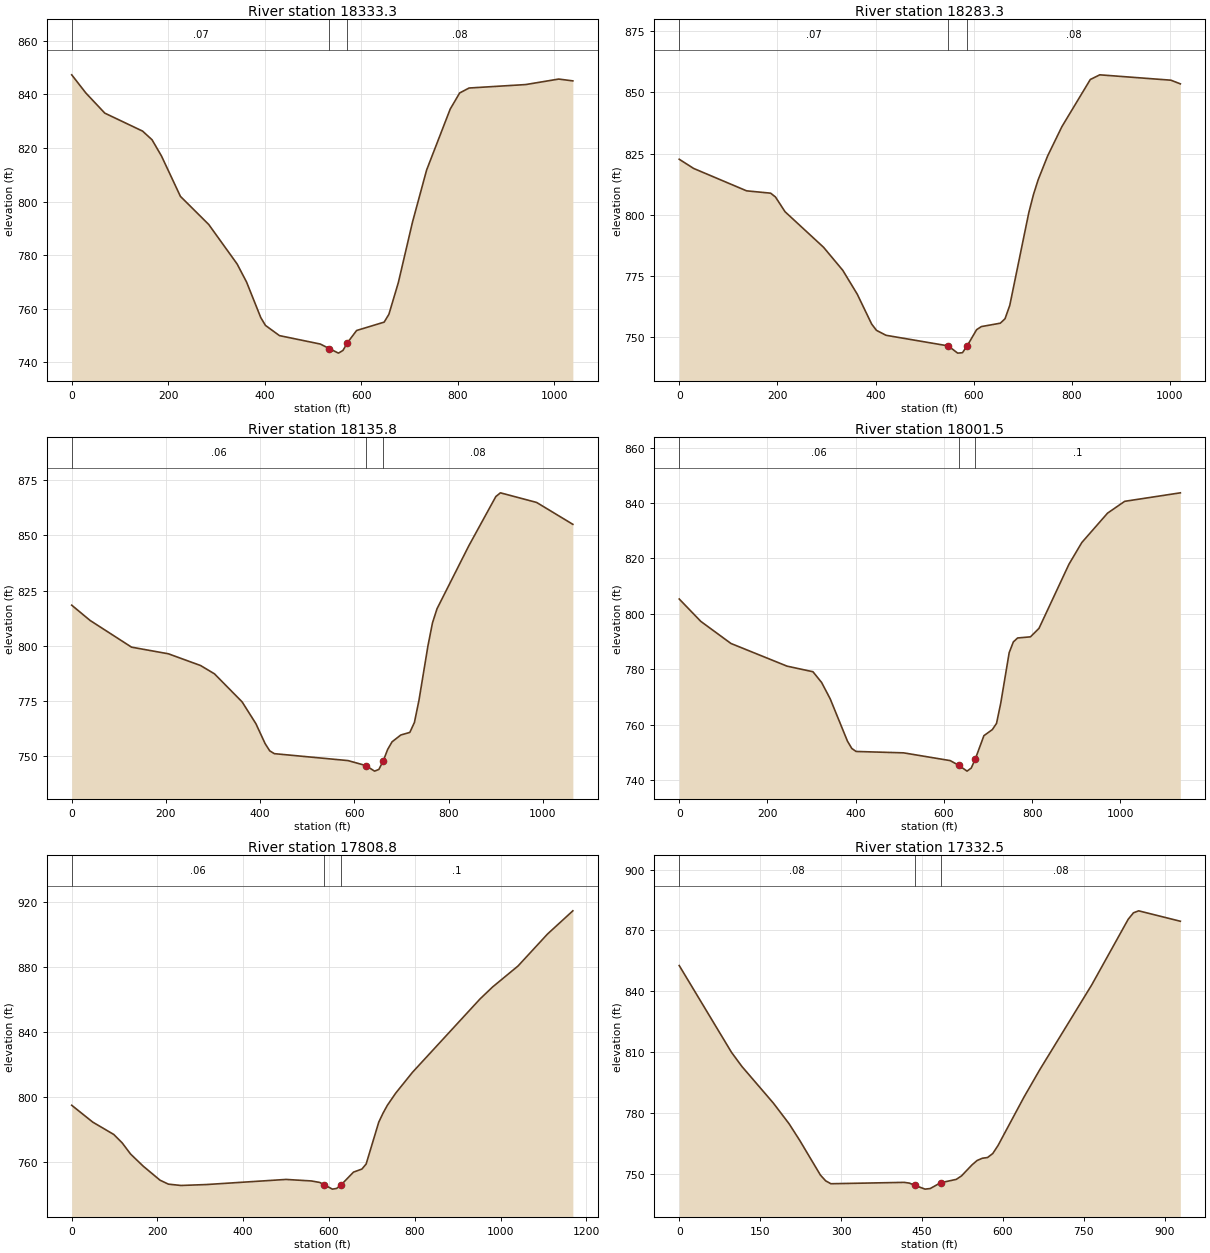
Type RM Length L Ch R = 1 ,18333.3 ,50,49.9,50.5
XS GIS Cut Line= 4
     1874385.712      645251.929     1874806.285      645274.064
     1875005.504      645218.075      1875415.66      645237.606
#Sta/Elev= 30
       0  847.25    29.4  840.45    68.6  832.96   146.9  826.26   166.5  823.03
   186.1  816.96   225.3  801.93     284  791.44   342.8  776.72   362.4  769.98
   391.8  756.75   401.6   753.8   430.6     750   515.2  746.86     534  745.16
   552.8  743.47   562.2  744.48   571.6  747.39   590.5  751.91   647.6  755.03
   657.4  757.94     677  769.78   706.3  792.31   735.6  811.75   784.5  834.48
   804.1  840.49   823.6  842.33     941  843.62  1009.4  845.67  1038.7  844.99
#Mann= 3 , 0 , 0
       0     .07       0     534    .045       0   571.6     .08       0
Bank Sta=534,571.6
XS Rating Curve= 0 ,0
Exp/Cntr=0.3,0.1

Type RM Length L Ch R = 1 ,18283.3 ,143.1,147.5,151.9
XS GIS Cut Line= 4
     1874387.014      645304.012     1874887.014      645301.408
     1875008.108      645268.856     1875403.942      645275.366
#Sta/Elev= 30
       0  822.73    29.4  818.98   137.3  809.84   186.3  808.89   196.1  807.34
   215.7  801.31   294.1  786.82   333.3  777.42   362.8  767.68   392.2  755.47
     402  752.91   421.6  750.89   548.2  746.57   567.5  743.62   577.2  743.79
   586.8  746.58   606.1   753.2   615.8  754.45   654.4  755.84     664  757.65
   673.7  763.15   712.3  800.82     722  808.37   731.6  814.42   750.9  824.12
   779.9  836.04   837.8  855.28   857.1  857.18    1002  854.99  1021.3   853.5
#Mann= 3 , 0 , 0
       0     .07       0   548.2    .045       0   586.8     .08       0
Bank Sta=548.2,586.8
XS Rating Curve= 0 ,0
Exp/Cntr=0.3,0.1

Type RM Length L Ch R = 1 ,18135.8 ,123.1,134.3,145.5
XS GIS Cut Line= 4
     1874361.015      645322.842     1874947.778       645427.71
     1875049.847      645421.268     1875412.177      645377.099
#Sta/Elev= 30
       0  818.38    39.1  811.44     127  799.34   205.2  796.33   273.6     791
   302.9  787.25   361.6  774.52   390.9  764.61   410.4   755.6   420.2  752.32
     430  751.04   586.3   747.9     624  745.65   642.6  743.12   651.8  743.89
   661.1  747.81   670.4  752.94   679.7   756.4   698.3   759.5   717.5  760.69
   727.2   765.2   736.8  775.17     756  800.05   765.6  810.41   775.2  816.78
   842.4  845.22     900  867.66   909.7  869.34   986.5  864.98  1063.4  855.05
#Mann= 3 , 0 , 0
       0     .06       0     624    .045       0   661.1     .08       0
Bank Sta=624,661.1
XS Rating Curve= 0 ,0
Exp/Cntr=0.3,0.1

Type RM Length L Ch R = 1 ,18001.5 ,186.2,192.7,199.3
XS GIS Cut Line= 4
     1874362.709       645356.53     1874878.334      645509.307
     1875086.667      645604.794      1875411.32      645780.141
#Sta/Elev= 30
       0  805.34    48.9  797.26   117.3  789.28   244.4   781.1   303.1  779.08
   322.7  775.22   342.2   769.3   381.3  754.03   391.1   751.4   400.9   750.3
   508.4   749.8   614.2     747   633.3  745.33   652.4   743.2   661.9  744.31
   671.5  747.75   690.6     756   709.7  758.19   719.2  760.43   728.8  767.75
   747.9  785.97   757.4  789.86     767  791.27   796.1  791.68   815.5  794.75
   883.5  817.92   912.6  825.74   970.9  836.34  1009.7   840.6  1135.9  843.67
#Mann= 3 , 0 , 0
       0     .06       0   633.3    .045       0   671.5      .1       0
Bank Sta=633.3,671.5
XS Rating Curve= 0 ,0
Exp/Cntr=0.3,0.1

Type RM Length L Ch R = 1 ,17808.8 ,476.8,476.3,476.3
XS GIS Cut Line= 3
     1874314.528      645404.449     1874803.681      645653.405
     1875267.223      646064.863
#Sta/Elev= 30
       0  795.07      49  784.71      98   777.1   117.6  771.94   137.2  765.06
   166.6   757.6   205.8  748.96   225.4   746.5   254.8  745.68   313.6  746.24
   499.9   749.4   558.7  748.47   578.4  747.55   588.2   746.2   607.9  743.43
   617.7  743.85   627.6  745.86   657.1   753.9   676.8   755.8   686.6  758.88
   716.1  784.72     726   790.2   735.8  794.93   755.5  802.52   794.8  815.41
   952.2  860.55   981.8  867.99  1040.8  880.84  1109.6  900.54  1168.7  914.83
#Mann= 3 , 0 , 0
       0     .06       0   588.2    .045       0   627.6      .1       0
Bank Sta=588.2,627.6
XS Rating Curve= 0 ,0
Exp/Cntr=0.3,0.1

Type RM Length L Ch R = 1 ,17332.5 ,391.2,400,410.6
XS GIS Cut Line= 3
      1874087.84      645614.677     1874442.859      645900.144
     1874795.185      646216.075
#Sta/Elev= 30
       0  852.68    96.9  809.88   116.3  802.88   174.5  784.85   203.6  774.67
   222.9  766.66   261.7  749.37   271.4  746.53   281.1   745.1   416.8  745.77
   426.5  745.41   436.2  744.37   455.6  742.44   465.2  742.73   484.5  745.59
   513.5  747.25   523.2  748.97   542.5  754.36   552.1  756.56   561.8  757.67
   571.4  758.02   581.1  759.99   590.8  763.92     639  787.83     668  801.22
   764.6  843.17   832.2  875.53   841.9  878.68   851.5  879.66   928.8  874.52
#Mann= 3 , 0 , 0
       0     .08       0   436.2    .045       0   484.5     .08       0
Bank Sta=436.2,484.5
XS Rating Curve= 0 ,0
Exp/Cntr=0.3,0.1

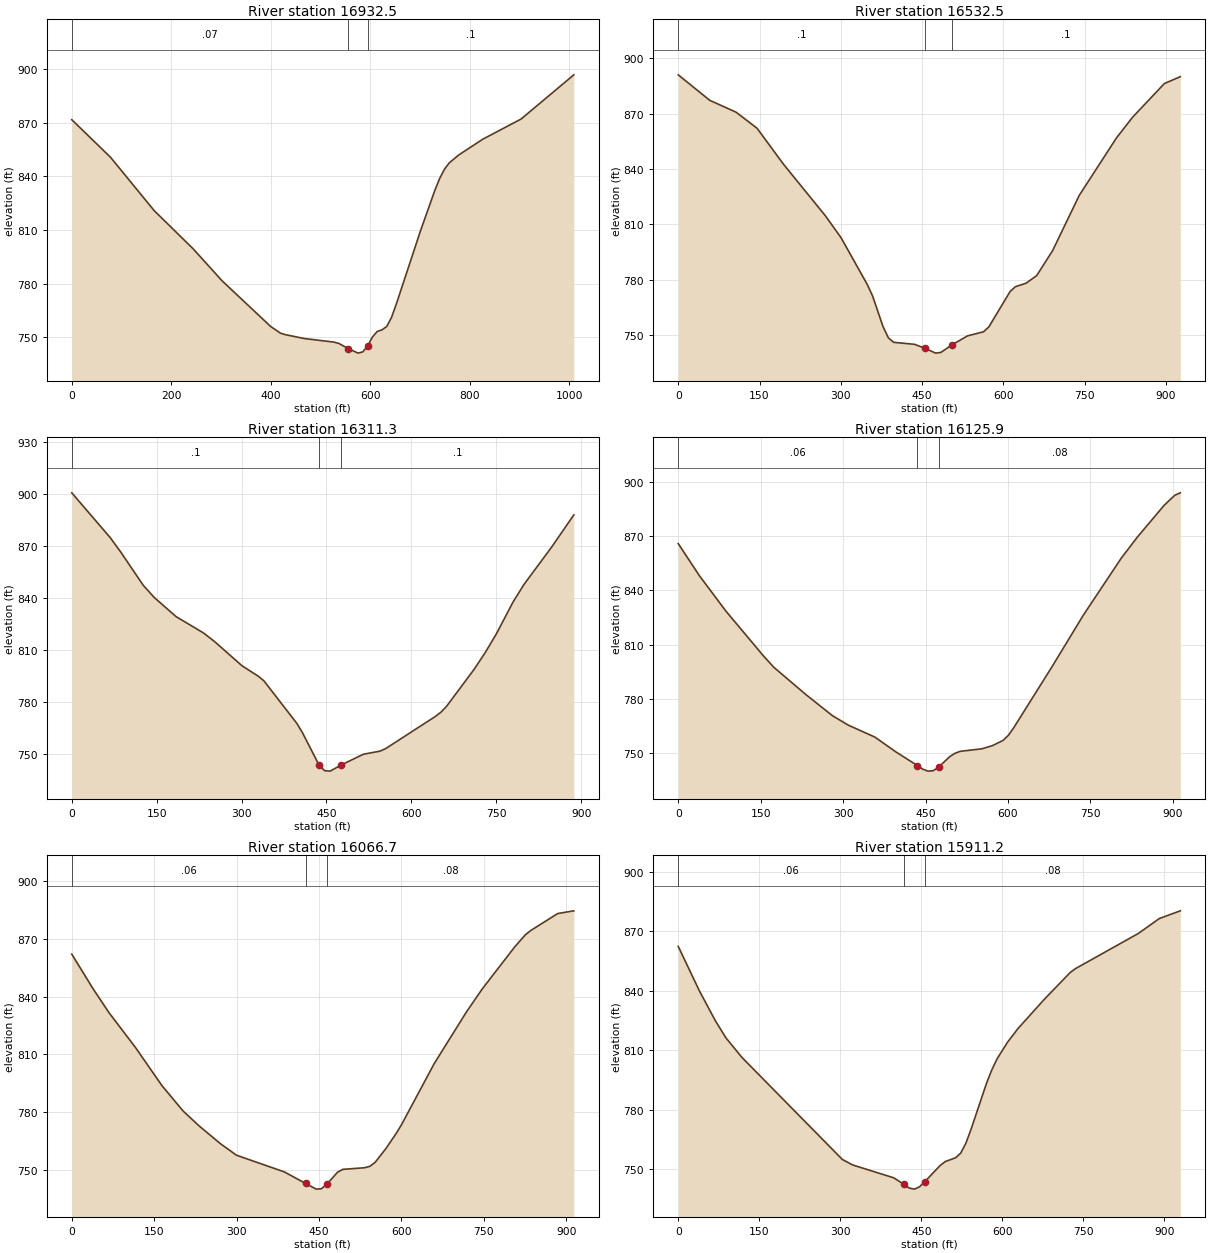
Type RM Length L Ch R = 1 ,16932.5 ,388.9,400,415.8
XS GIS Cut Line= 3
     1873989.971      645727.048     1874270.128      646229.348
     1874427.814      646633.472
#Sta/Elev= 30
       0  871.66      78   850.6   165.7  820.79   243.7  799.52   302.2  781.53
   399.7  756.04   419.2  752.33   428.9  751.48   467.9  749.27   526.4  747.32
   536.2  746.62   555.6  743.71   575.2  741.14   584.8  741.84   594.4   745.1
   604.1  750.12   613.7  753.24   623.4  754.15     633  756.06   642.6  761.14
   652.3  768.68   700.5  809.31   729.4  832.01     739  838.61   748.7  843.86
   758.3  847.44   777.6  851.93   825.8  860.73   902.9  872.03  1008.9  896.74
#Mann= 3 , 0 , 0
       0     .07       0   555.6    .045       0   594.4      .1       0
Bank Sta=555.6,594.4
XS Rating Curve= 0 ,0
Exp/Cntr=0.3,0.1

Type RM Length L Ch R = 1 ,16532.5 ,216.7,221.3,218
XS GIS Cut Line= 3
     1873885.503      645736.741     1873887.525      646211.643
      1873741.61      646638.901
#Sta/Elev= 30
       0  890.97    58.2  877.16   106.6  870.76   145.4  862.07   193.8  842.73
   271.4   814.7   300.4  802.81   348.9  777.42   358.6  771.25     378  754.58
   387.7   748.6   397.4  746.17   436.1  745.07   455.5  742.92   474.9  740.31
   484.7   740.7   504.4  744.68   533.8  749.65   563.2  751.85   573.1   754.5
   612.3  773.64   622.1  776.28   641.8  778.16   661.4  782.28   690.8  795.82
   739.9  825.69   808.6  856.82   838.1  867.94     897  886.25   926.4  889.97
#Mann= 3 , 0 , 0
       0      .1       0   455.5    .045       0   504.4      .1       0
Bank Sta=455.5,504.4
XS Rating Curve= 0 ,0
Exp/Cntr=0.3,0.1

Type RM Length L Ch R = 1 ,16311.3 ,184.5,185.4,183.7
XS GIS Cut Line= 3
     1873736.407      645715.037      1873686.06      646090.037
      1873592.31      646590.037
#Sta/Elev= 30
       0  900.64    67.9  874.85    87.3  866.17   126.1  847.45   145.5  840.42
   184.3  829.33   232.8   819.9   252.2  814.99   300.8  801.02   329.9  794.92
   339.6   792.3   397.9  767.73   407.7   762.4   437.1  743.68   446.8  740.58
   456.6  740.32   476.2  743.89   515.3  750.06   544.7  751.84   554.5  753.27
   642.5  771.83   652.3  774.28   662.1   777.6     711  799.01   730.6  808.67
   750.1  819.31   779.5  837.63     799  847.85     848  869.45   887.1  887.95
#Mann= 3 , 0 , 0
       0      .1       0   437.1    .045       0   476.2      .1       0
Bank Sta=437.1,476.2
XS Rating Curve= 0 ,0
Exp/Cntr=0.3,0.1

Type RM Length L Ch R = 1 ,16125.9 ,59.1,59.1,60.2
XS GIS Cut Line= 3
     1873585.568      645694.711     1873489.888      646138.979
      1873440.37      646595.554
#Sta/Elev= 30
       0  865.87    38.7  848.05      87  828.45   154.7  803.91     174  797.48
   232.1  782.45   280.4  770.79   309.4  765.51   357.8   758.9   396.4  750.64
   435.1  743.18   444.8   741.2   454.4  740.07   464.2   740.3     474  742.32
   493.5  747.93   503.3  749.89   513.1  751.01   552.2  752.39   571.7  754.15
   591.2  757.07     601  759.93   610.8  764.18   679.2  797.29   737.8  826.56
   806.2   857.8   835.5  869.45   884.4  887.09   903.9  892.66   913.7  893.94
#Mann= 3 , 0 , 0
       0     .06       0   435.1    .045       0     474     .08       0
Bank Sta=435.1,474
XS Rating Curve= 0 ,0
Exp/Cntr=0.3,0.1

Type RM Length L Ch R = 1 ,16066.7 ,159.7,155.5,152.8
XS GIS Cut Line= 3
     1873525.673      645692.107     1873429.992      646136.375
     1873380.474       646592.95
#Sta/Elev= 30
       0  862.03    38.7   844.1    67.7  831.69     116   813.6   164.4  793.72
     203  780.55   232.1  772.85   270.7  763.68   299.8  757.73   386.8  749.08
   425.4  743.12   444.8  740.14   454.4  740.35   464.2  742.71   483.8  748.95
   493.5  750.41   532.6  751.22   542.4  751.96   552.2  754.06   571.7  761.19
   591.2  769.38     601  774.04   659.6  805.25   718.3  832.09   747.6  844.22
   806.2  865.84   825.8  872.18   835.5  874.34   884.4  883.11   913.7  884.51
#Mann= 3 , 0 , 0
       0     .06       0   425.4    .045       0   464.2     .08       0
Bank Sta=425.4,464.2
XS Rating Curve= 0 ,0
Exp/Cntr=0.3,0.1

Type RM Length L Ch R = 1 ,15911.2 ,192.8,178.7,168.1
XS GIS Cut Line= 4
     1873252.032      645669.898     1873285.018      645952.884
     1873274.601      646228.925     1873356.198        646588.3
#Sta/Elev= 30
       0  862.46    39.3  839.95    68.8  824.94    88.4  816.29   117.9  806.46
     304  754.96     323  752.21   399.2  745.71   418.3  742.37   427.8  740.56
   437.3  740.02   446.8  741.18   456.4  743.74   484.9  751.91   494.5  753.93
   513.5  755.83     523  758.15   532.6  763.15   542.1  770.11   570.8  793.38
   580.5  800.07   590.2  805.63   609.6  814.05     629  820.96   677.5  835.66
     726  849.33   735.7  851.26   852.1  868.99   890.9  876.51   929.7  880.39
#Mann= 3 , 0 , 0
       0     .06       0   418.3    .045       0   456.4     .08       0
Bank Sta=418.3,456.4
XS Rating Curve= 0 ,0
Exp/Cntr=0.3,0.1

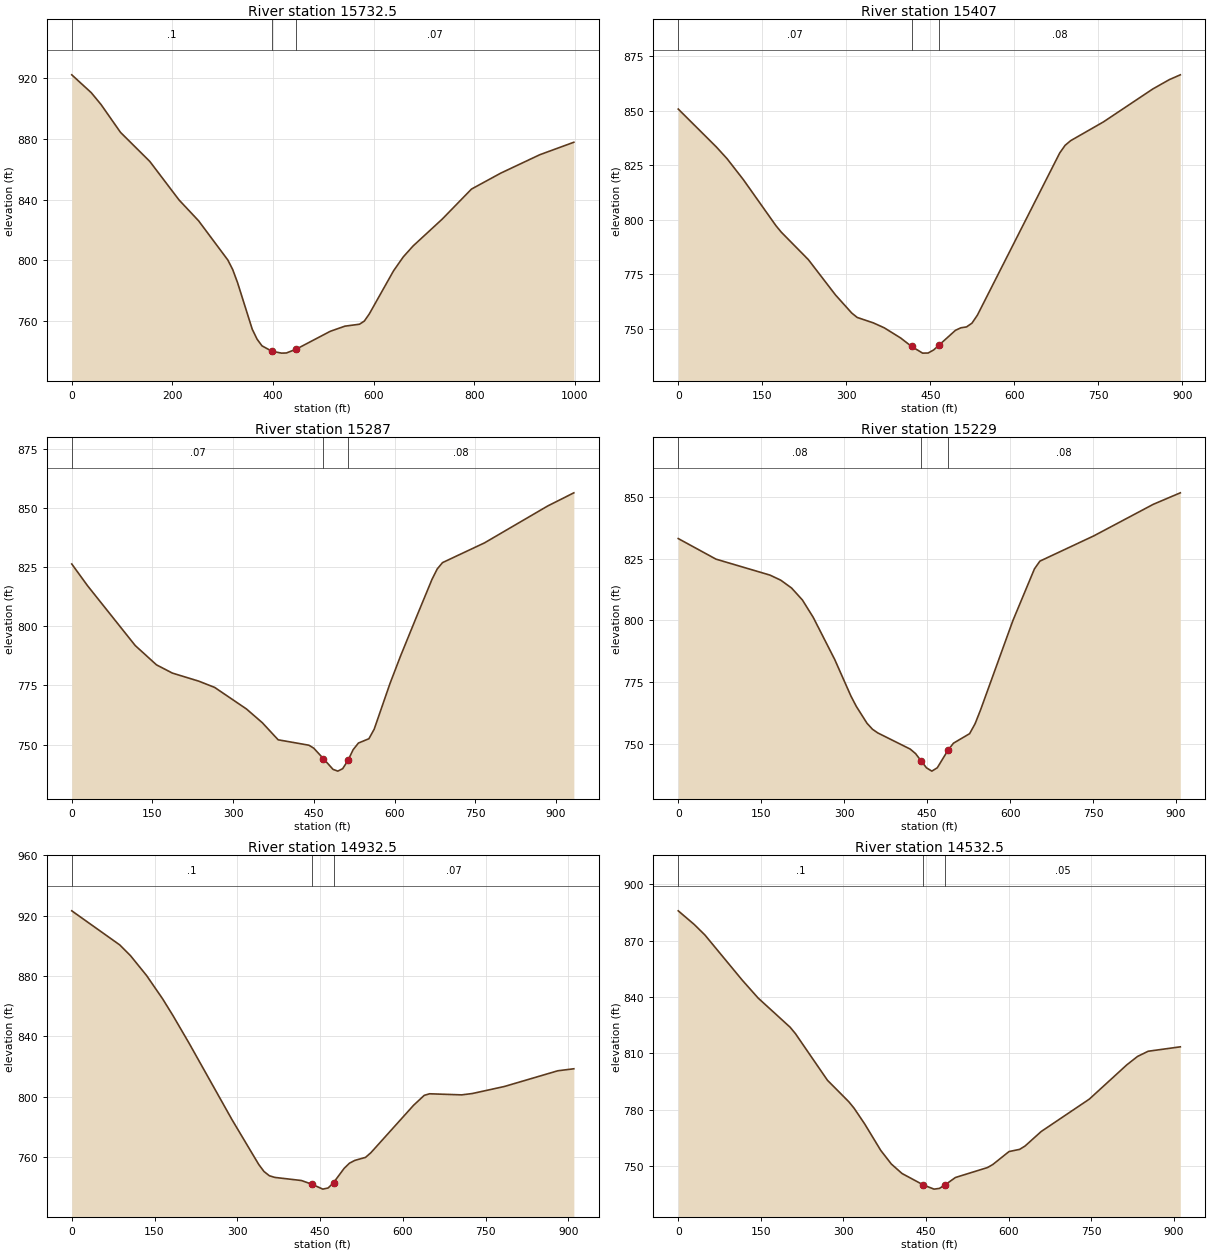
Type RM Length L Ch R = 1 ,15732.5 ,329.4,325.5,317.4
XS GIS Cut Line= 3
     1872864.162      645722.125       1873106.1      646085.068
     1873337.623      646596.714
#Sta/Elev= 30
       0   922.1    38.8  910.33    58.2  902.53    96.9  884.21   155.1  865.08
   213.2  839.72     252  826.02   310.2  800.17   319.9  793.85   329.6  785.16
   358.6  754.68   368.3  748.05     378  743.69   397.4  740.17   416.8  738.88
   426.5  738.97   445.9  741.46   513.6  753.23   542.7  756.62   571.8  757.91
   581.4  759.98   591.1  764.58   639.5  793.07   658.9  802.27   678.3  809.42
   736.4  827.16   794.4  846.89   852.5  857.37     930  869.48   997.8  877.71
#Mann= 3 , 0 , 0
       0      .1       0   397.4    .045       0   445.9     .07       0
Bank Sta=397.4,445.9
XS Rating Curve= 0 ,0
Exp/Cntr=0.3,0.1

Type RM Length L Ch R = 1 ,15407   ,121.1,120,119.1
XS GIS Cut Line= 3
     1872619.653      646039.255      1872886.58      646306.182
     1873253.334      646672.936
#Sta/Elev= 30
       0  850.85    67.8   833.5    87.1  828.06   116.2  818.44   174.2  797.35
   183.9  794.31   232.3  781.67   280.7  765.45   309.7  757.14   319.4  755.13
   348.4  752.61   367.8  750.35   397.1  745.67   416.6  741.78   436.2  738.73
     446  738.78   455.8  740.16   465.6  742.43   494.9  749.22   504.7  750.38
   514.5  750.76   524.3  752.49   534.1  756.22   680.9  830.65   690.6  834.19
   700.4  836.31   759.2  844.98   847.2  860.09   876.6  864.36   896.2  866.57
#Mann= 3 , 0 , 0
       0     .07       0   416.6    .045       0   465.6     .08       0
Bank Sta=416.6,465.6
XS Rating Curve= 0 ,0
Exp/Cntr=0.3,0.1

Type RM Length L Ch R = 1 ,15287   ,58,58,57.8
XS GIS Cut Line= 4
     1872558.889      646063.127     1872813.346      646400.966
     1872871.823      646456.356     1873180.851      646754.967
#Sta/Elev= 30
       0  826.24    29.5  817.01     118  791.79   157.4  783.66   186.9  780.18
   236.1  776.76   265.6  774.12   324.6  765.03   354.1  759.23   383.6     752
   440.8  749.71   449.8  748.46   467.7  744.04   485.6  739.52   494.5  738.77
   503.5   739.8   513.3  743.26     523  747.83   532.8  750.63   552.3  752.45
   562.1  756.48   591.4  775.72   610.9  787.28   640.2  803.61   669.5  819.72
   679.3  824.15   689.1  826.82   767.2  835.16   884.4  850.71   933.2  856.29
#Mann= 3 , 0 , 0
       0     .07       0   467.7    .045       0   513.3     .08       0
Bank Sta=467.7,513.3
XS Rating Curve= 0 ,0
Exp/Cntr=0.3,0.1

Type RM Length L Ch R = 1 ,15229   ,294.4,296.5,298.7
XS GIS Cut Line= 3
     1872484.412      646167.998     1872831.459      646496.721
     1873140.487      646795.332
#Sta/Elev= 30
       0  833.09    68.3  824.74   165.8  818.28   185.4  816.21   204.9  813.04
   224.4  808.22   243.9  801.21   282.9  784.07   312.2  769.25   321.9  765.07
   341.4  758.17   351.2  755.78     361  754.27   419.5  747.73   429.2  745.89
     439  742.99   448.8  740.16   458.5  738.81   468.3  740.16   487.8  747.33
   497.6  750.14   526.8     754   536.6  757.99   546.4  763.52     605  799.82
     644   820.8   653.8  823.93   751.5   834.2   858.9  846.98   907.7  851.63
#Mann= 3 , 0 , 0
       0     .08       0     439    .045       0   487.8     .08       0
Bank Sta=439,487.8
XS Rating Curve= 0 ,0
Exp/Cntr=0.3,0.1

Type RM Length L Ch R = 1 ,14932.5 ,408.7,400,389.3
XS GIS Cut Line= 3
     1872287.002      646327.708     1872586.905      646669.882
     1872886.807      647012.057
#Sta/Elev= 30
       0  923.13    87.1  900.51   106.5  893.39   135.5  880.31   164.6  864.86
   183.9  853.44     213  835.19   290.4  784.78   338.8  755.13   348.5  750.38
   358.2  747.59   367.9  746.51   416.3  744.44   435.6  741.93     455  738.74
   464.7  739.51   474.4  742.99   493.7  752.52   503.4  755.95   513.1  757.78
   532.4  759.77   542.1  762.85   619.6  794.33   638.9  800.89   648.6  801.91
   706.7  801.19   726.1  802.09   784.2  806.75     881  817.16     910  818.48
#Mann= 3 , 0 , 0
       0      .1       0   435.6    .045       0   474.4     .07       0
Bank Sta=435.6,474.4
XS Rating Curve= 0 ,0
Exp/Cntr=0.3,0.1

Type RM Length L Ch R = 1 ,14532.5 ,330.8,319.2,309.5
XS GIS Cut Line= 3
     1871939.262      646778.325     1872345.927      646981.682
     1872769.784      647152.104
#Sta/Elev= 30
       0  885.87      29  878.62    48.4  873.02   116.1     849   145.1  839.42
   203.2  823.88   212.8  820.47   270.9  795.66   309.6  784.24   319.2  780.81
   338.6  772.36   367.6  758.35     387  751.03   406.3  746.02     445  739.92
   464.4   737.7   474.1  738.08   483.8  739.83   503.3   743.9   561.6   749.2
   571.3  750.85   600.5   757.7   619.9  758.88   629.6  760.64   658.8  768.34
   746.3  785.62   814.3  803.85   833.8  808.34   853.2  811.11   911.5  813.46
#Mann= 3 , 0 , 0
       0      .1       0     445    .045       0   483.8     .05       0
Bank Sta=445,483.8
XS Rating Curve= 0 ,0
Exp/Cntr=0.3,0.1