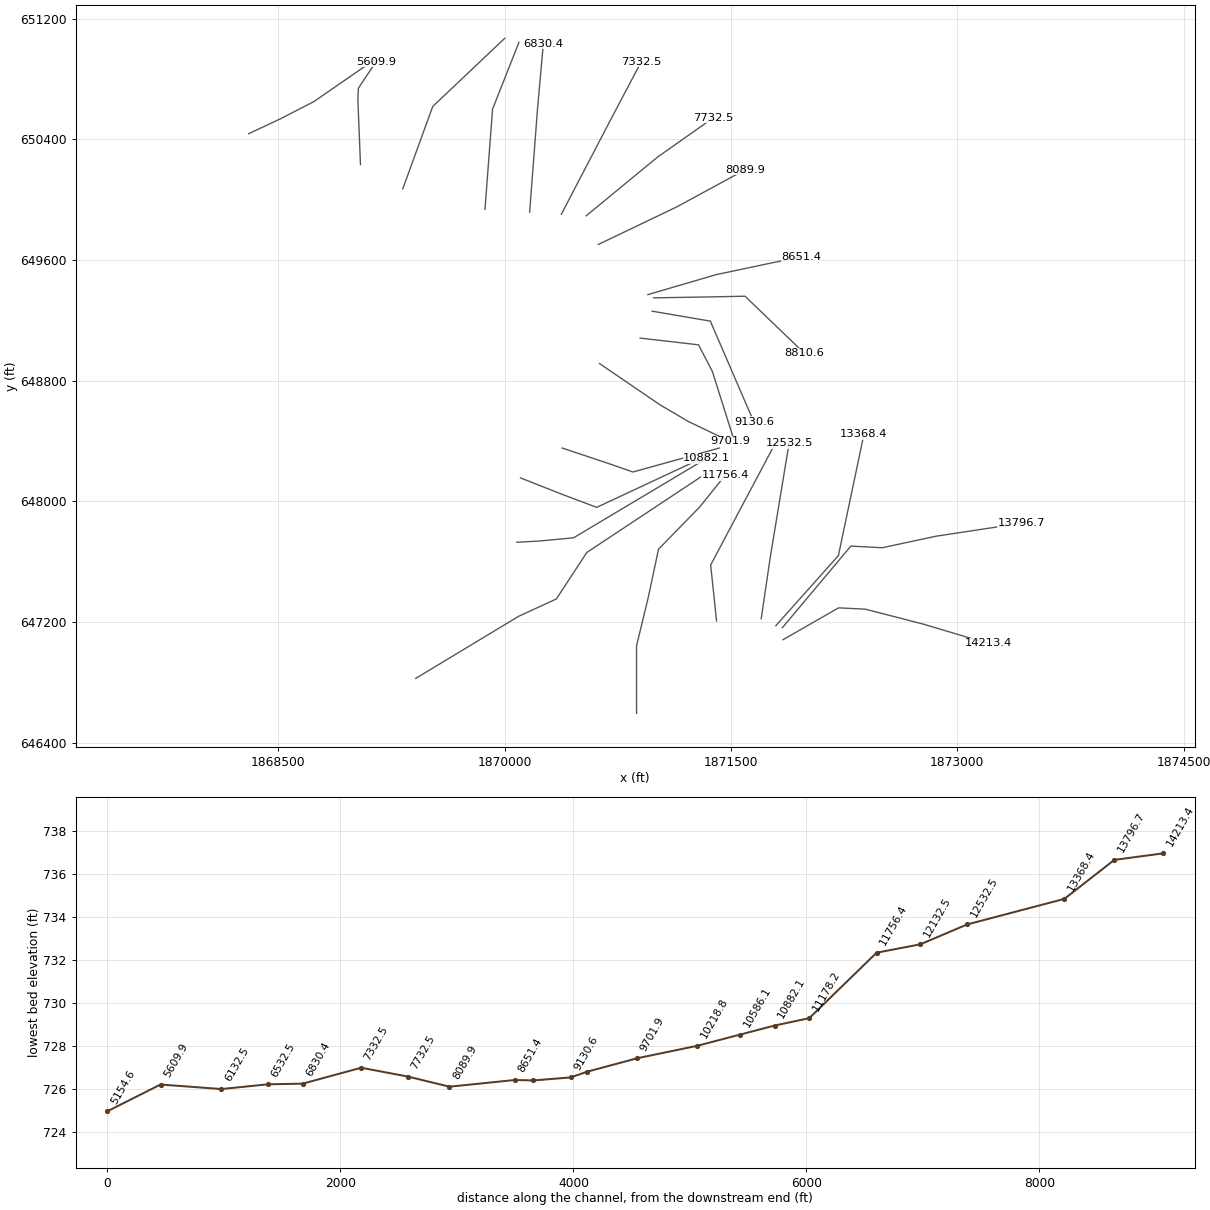
HEC-RAS study LFSpringCk.prj: LFSpringCk

--- LFSpringCk.g01 (geometry) --- (continued)

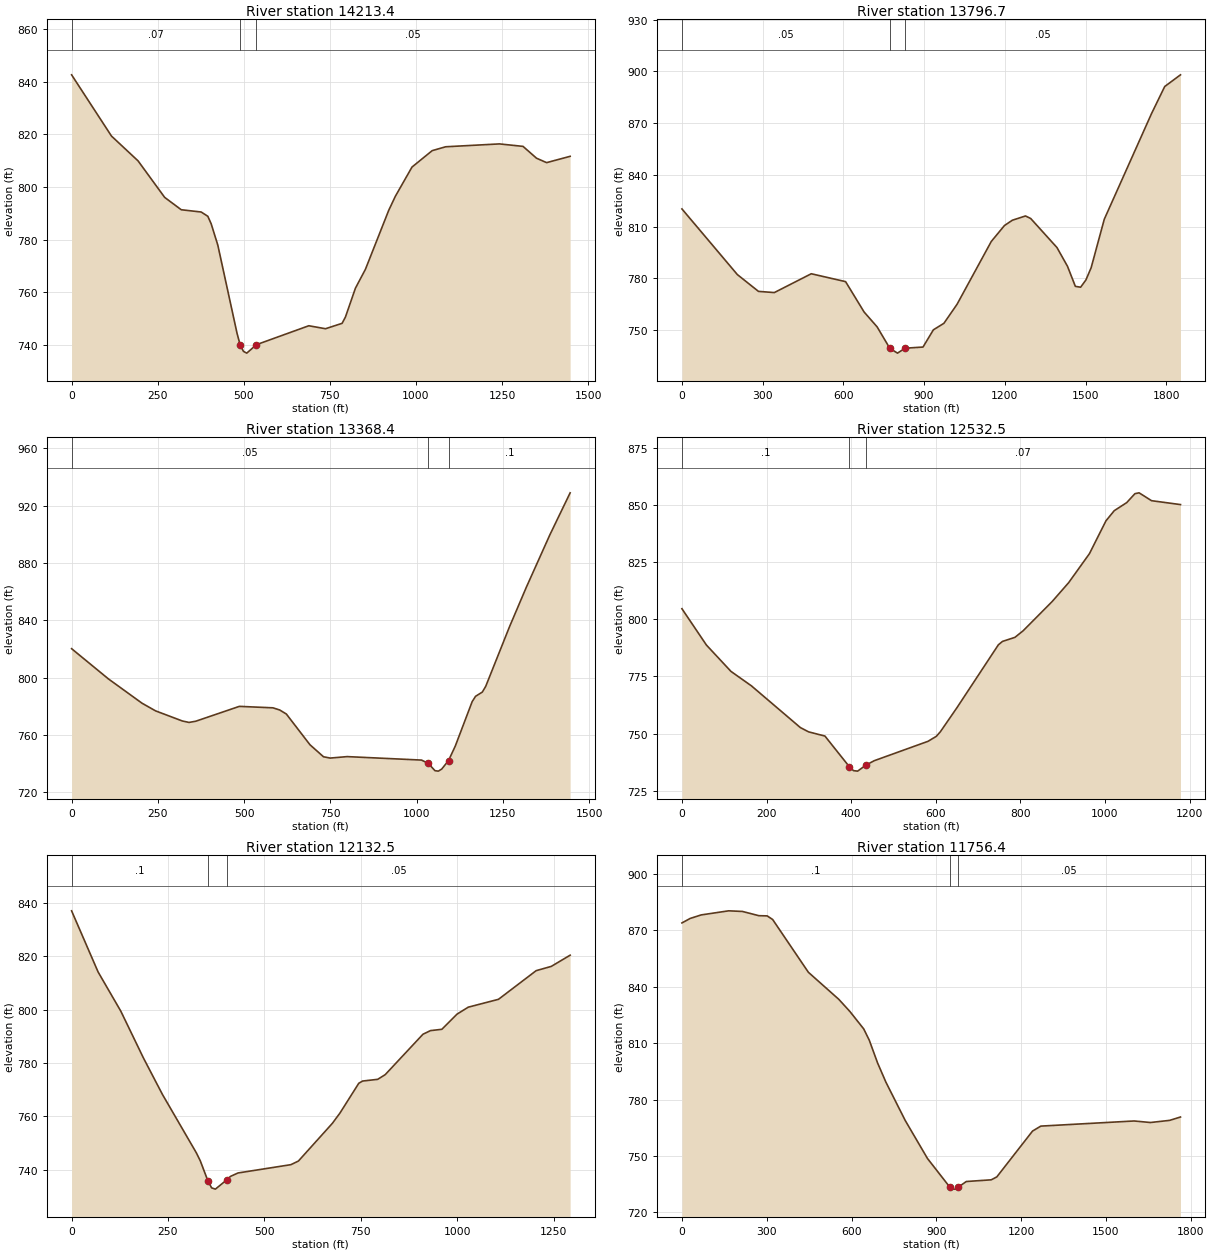
Type RM Length L Ch R = 1 ,14213.4 ,416.6,416.7,416.6
XS GIS Cut Line= 5
     1871845.004      647084.051     1872213.403      647295.115
     1872390.487      647286.434     1872774.167      647187.476
      1873204.94      647058.983
#Sta/Elev= 30
       0  842.57   115.8  819.33     193  809.91   270.2  796.06   318.4  791.36
   376.3   790.5   395.6  788.87   405.3  786.03   424.6  777.92   480.6  744.35
   489.9  739.86   499.2  737.59   508.6  736.94   536.6  740.14   688.8  747.33
   737.2   746.2   785.5  748.25   795.2  750.66   824.2   761.6   853.2  768.76
   920.8  791.13   940.1  796.48   988.4  807.56    1047  813.79  1086.1  815.26
  1242.4  816.35  1310.8  815.41  1349.9  810.93  1379.2  809.24  1447.6  811.64
#Mann= 3 , 0 , 0
       0     .07       0   489.9    .045       0   536.6     .05       0
Bank Sta=489.9,536.6
XS Rating Curve= 0 ,0
Exp/Cntr=0.3,0.1

Type RM Length L Ch R = 1 ,13796.7 ,396.1,428.3,460.5
XS GIS Cut Line= 5
     1871840.505      647163.284     1872294.567      647704.403
       1872502.9      647693.552     1872856.633      647769.507
     1873426.294      647855.858
#Sta/Elev= 30
       0  820.25     206  782.18   284.5  772.44   343.4  771.75   480.7  782.66
   608.3  778.09     677   760.5   725.4  751.88   772.8   739.4   801.2  736.64
   829.7   739.5     896  740.16   934.6  750.15   973.7  753.93  1022.6  764.97
  1149.7  801.36  1198.6   810.6  1227.9  813.68  1276.8  816.17  1296.3   814.7
    1394  797.84    1433     787  1462.3  775.35  1481.9  774.86  1501.4  779.05
  1520.9  786.13  1569.8  814.28  1745.5  875.56  1794.4  891.22    1853     898
#Mann= 3 , 0 , 0
       0     .05       0   772.8    .045       0   829.7     .05       0
Bank Sta=772.8,829.7
XS Rating Curve= 0 ,0
Exp/Cntr=0.3,0.1

Type RM Length L Ch R = 1 ,13368.4 ,834.7,835.9,836.4
XS GIS Cut Line= 3
     1871797.605      647177.059     1872212.101      647641.469
     1872381.372       648446.59
#Sta/Elev= 30
       0  820.28     107  799.14   204.2  782.22   243.2   776.9     321  769.82
   340.4  768.81   359.9  769.65   486.3  780.02   583.6     779     603  777.52
   622.5  774.69     691  753.23   730.2  744.85   749.8  743.94   798.8  744.96
  1014.2  742.54  1033.8  740.29  1053.4  735.13  1063.2  734.83    1073  736.29
  1092.6   742.2  1112.2  752.29  1161.2  783.32    1171  787.04  1190.6  789.99
  1200.4  793.96  1268.9  835.27  1317.9  862.98  1386.4  899.71  1445.2  929.03
#Mann= 3 , 0 , 0
       0     .05       0  1033.8    .045       0  1092.6      .1       0
Bank Sta=1033.8,1092.6
XS Rating Curve= 0 ,0
Exp/Cntr=0.3,0.1

Type RM Length L Ch R = 1 ,12532.5 ,394.5,400,391.1
XS GIS Cut Line= 3
     1871700.654      647223.652     1871759.558      647624.913
     1871885.541      648387.393
#Sta/Elev= 30
       0  804.59    57.9  788.72   115.9  777.21   164.2   770.9     280  752.66
   299.3   750.8     338  748.96   395.9  735.53   405.6  733.85   415.3  733.64
   434.9  736.27   454.5  738.19   581.6  746.66   601.2  748.83     611  750.88
   650.1  761.37     748  788.84   757.7  790.31   787.1  792.08   806.6  794.98
   875.1  807.73   914.2     816   963.2  828.64  1002.3     843  1021.9  847.43
  1051.2  850.93  1070.8  854.86  1080.6  855.22  1109.9  851.79  1178.4  850.08
#Mann= 3 , 0 , 0
       0      .1       0   395.9    .045       0   434.9     .07       0
Bank Sta=395.9,434.9
XS Rating Curve= 0 ,0
Exp/Cntr=0.3,0.1

Type RM Length L Ch R = 1 ,12132.5 ,383.7,376.2,383.8
XS GIS Cut Line= 3
     1871404.573      647208.285     1871365.512      647579.177
     1871796.816      648391.801
#Sta/Elev= 30
       0  837.06    68.7  814.15   127.6  799.45   186.5  781.83   235.5  768.25
   323.9  746.23   333.7  743.34   353.3  735.89   363.1   733.2   372.9  732.72
   402.3  736.18   412.1   737.5   431.7  738.78   568.7  741.89   588.3  743.26
   676.3  757.39   695.9  761.23   744.8  772.41   754.6  773.24   793.8  773.88
   813.4  775.65   911.2  790.79   930.8  792.15   960.2  792.64   999.3   798.3
  1028.7  800.94    1107  803.88  1204.8  814.63    1244  816.23  1292.9  820.43
#Mann= 3 , 0 , 0
       0      .1       0   353.3    .045       0   402.3     .05       0
Bank Sta=353.3,402.3
XS Rating Curve= 0 ,0
Exp/Cntr=0.3,0.1

Type RM Length L Ch R = 1 ,11756.4 ,586.9,578.2,569.5
XS GIS Cut Line= 6
       1870874.5      646595.817     1870874.199      647043.177
     1870952.553      647366.903     1871019.827      647683.743
      1871291.61      647962.236     1871461.233      648172.892
#Sta/Elev= 30
       0  873.93    29.2  876.32    68.1  878.19   165.3  880.37     214  880.04
   272.3  877.78   301.5  877.68   320.9  875.77   447.4  847.68   555.1  833.28
   594.3  826.82   643.3  817.53   662.9  811.53   692.3  799.42   721.7  789.22
   790.2   768.8   868.8  748.62   947.3  733.49   957.1  732.37   966.9  732.33
   976.7  733.29  1006.2  736.38  1094.5  737.28  1114.1  738.84  1240.5  763.22
  1269.7  765.85  1599.7  768.58  1657.7  767.77  1725.3   768.9  1763.9  770.69
#Mann= 3 , 0 , 0
       0      .1       0   947.3    .045       0   976.7     .05       0
Bank Sta=947.3,976.7
XS Rating Curve= 0 ,0
Exp/Cntr=0.3,0.1

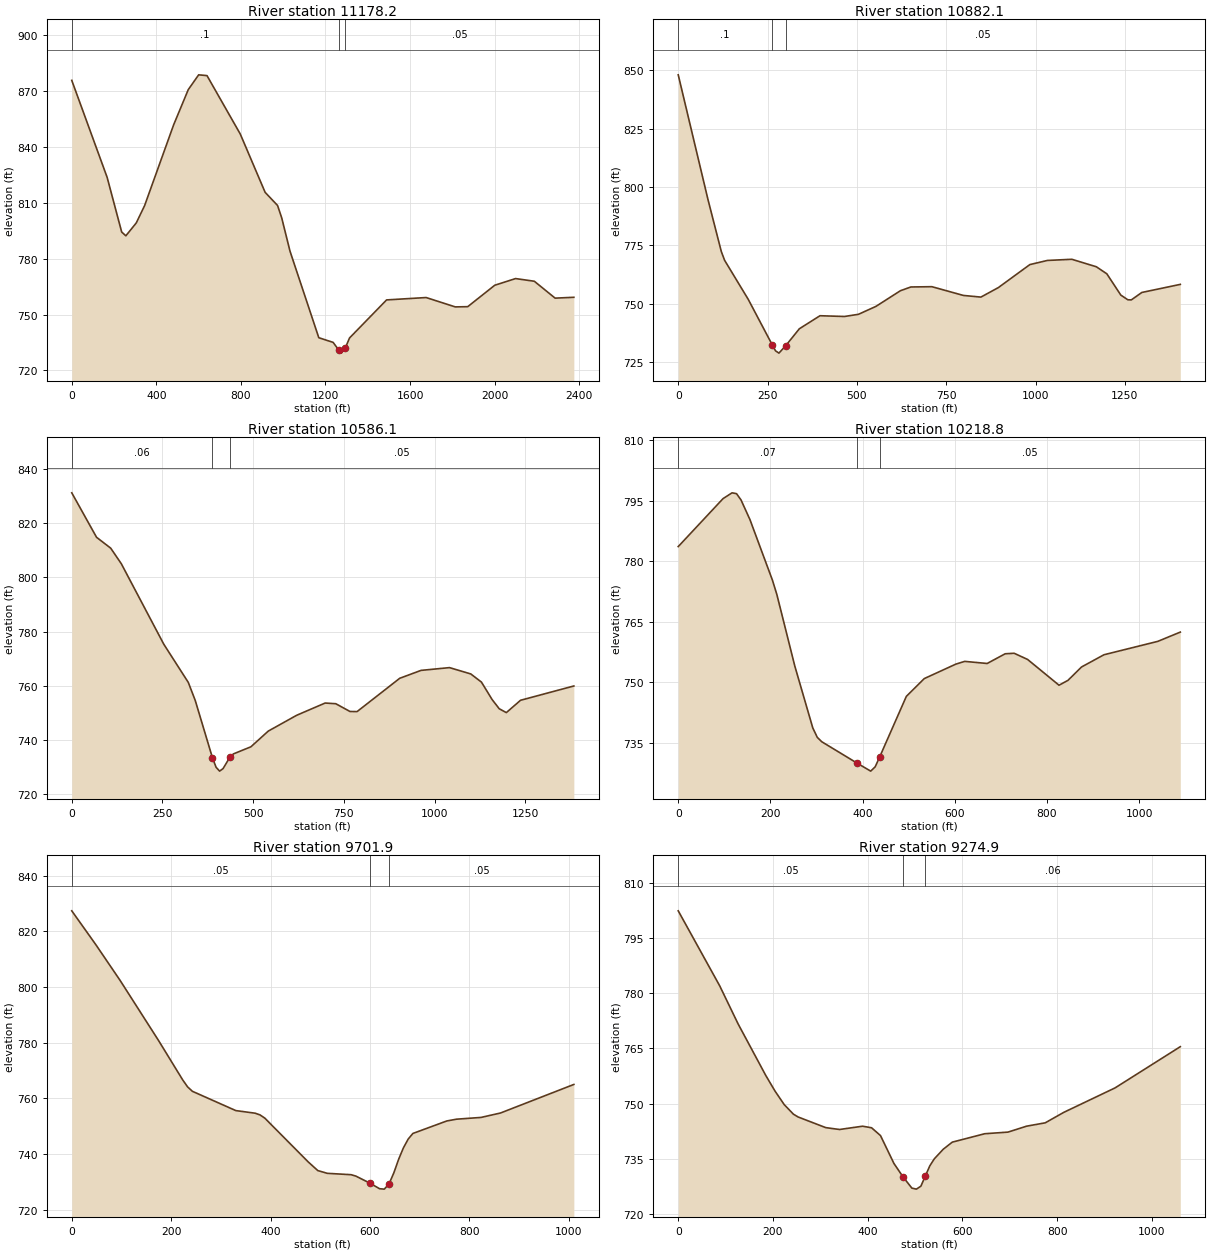
Type RM Length L Ch R = 1 ,11178.2 ,315.9,296.1,275.8
XS GIS Cut Line= 5
     1869410.958      646827.588     1870093.307      647239.387
     1870342.744      647353.882     1870544.567      647662.042
     1871323.875      648178.397
#Sta/Elev= 30
       0  875.85   167.3  823.74   236.1  794.36   255.8  792.34     305  799.24
   344.4  808.52   482.1  852.04     551  870.87   600.2  878.83   639.6  878.41
     797  847.02   914.6  815.68   973.4  808.62     993  801.97  1032.2  784.09
  1168.4  737.57  1236.2  735.06  1261.8   731.1    1275  729.29  1294.4  732.28
  1313.8  737.44    1489  757.88    1676  759.16  1813.8  754.13  1872.8  754.25
  2000.7  765.77  2099.1  769.35  2187.7  767.92  2286.1  758.84  2374.7  759.29
#Mann= 3 , 0 , 0
       0      .1       0  1261.8    .045       0  1294.4     .05       0
Bank Sta=1261.8,1294.4
XS Rating Curve= 0 ,0
Exp/Cntr=0.3,0.1

Type RM Length L Ch R = 1 ,10882.1 ,305.6,295.9,286.3
XS GIS Cut Line= 4
     1870081.346      647729.733     1870229.462      647737.997
     1870457.195      647759.474      1871339.99      648286.355
#Sta/Elev= 30
       0  847.96    83.4  794.53   120.5  772.42   129.8  768.64     196  751.93
   262.7  732.61   272.2  729.95   281.8  728.95   300.8  732.12     339  739.37
   396.7  744.94   465.2  744.62   504.4  745.55   553.3  748.93   621.9  755.64
   651.2  757.24     710  757.36   798.1  753.62   847.1  752.91     896  756.98
   984.1  766.81  1033.1  768.58  1101.6  769.08  1170.2  765.88  1199.6  762.86
  1238.7  753.77  1258.3  751.77  1268.1  751.71  1297.5  754.89  1405.2  758.35
#Mann= 3 , 0 , 0
       0      .1       0   262.7    .045       0   300.8     .05       0
Bank Sta=262.7,300.8
XS Rating Curve= 0 ,0
Exp/Cntr=0.3,0.1

Type RM Length L Ch R = 1 ,10586.1 ,367.2,367.3,367.1
XS GIS Cut Line= 4
      1870105.33      648156.399     1870368.351      648052.233
     1870610.539      647961.087      1871373.56      648317.858
#Sta/Elev= 30
       0  831.13    68.3  814.74   107.3  810.73   136.6  804.98   253.6  775.33
   321.2  761.24   340.4  754.57   387.9   733.4   397.9  729.94   407.5  728.53
   417.1  729.47   436.2  733.74   445.8  734.89   493.8   737.5   541.7  743.29
     620  749.12   698.4  753.63   727.8  753.38   766.9  750.52   786.5  750.48
   904.1  762.76   962.8  765.67  1041.2  766.69  1099.9  764.36  1129.3  761.35
  1158.7  754.92  1178.3  751.53  1197.9   750.1  1237.1  754.65    1384  759.92
#Mann= 3 , 0 , 0
       0     .06       0   387.9    .045       0   436.2     .05       0
Bank Sta=387.9,436.2
XS Rating Curve= 0 ,0
Exp/Cntr=0.3,0.1

Type RM Length L Ch R = 1 ,10218.8 ,521.1,517,512.8
XS GIS Cut Line= 4
     1870381.372      648354.316      1870686.06      648252.754
     1870850.122      648195.462     1871423.039      648354.316
#Sta/Elev= 30
       0   783.6    97.3  795.48   116.8  796.91   126.5   796.7   136.2  795.16
   155.7  790.26   204.4  775.29   214.1   771.7     253  754.01     292   738.7
   301.7  736.38   311.4  735.29   388.8  729.94   417.7  728.01   427.4  729.08
     437  731.49     495  746.52   533.9  750.92   602.2  754.49   621.6  755.18
   670.4  754.66   709.4  757.06   728.9  757.19   758.1  755.66   826.3  749.28
   845.8  750.49   875.1  753.79   923.8  756.82  1040.8  760.14  1089.5  762.43
#Mann= 3 , 0 , 0
       0     .07       0   388.8    .045       0     437     .05       0
Bank Sta=388.8,437
XS Rating Curve= 0 ,0
Exp/Cntr=0.3,0.1

Type RM Length L Ch R = 1 ,9701.9  ,440.5,427,413.5
XS GIS Cut Line= 4
     1870628.768      648914.212      1871029.81      648640.774
     1871219.418      648529.271      1871494.35      648397.762
#Sta/Elev= 30
       0  827.34    48.5  815.17    97.1   802.4   174.7  780.75   223.3  766.61
     233  764.15   242.7  762.55   330.1  755.62   368.9  754.69   378.6  754.09
   388.3  752.93   475.7   737.2     495  734.09   514.1   733.1   561.9  732.61
   571.5  732.11   600.2  729.54   619.3  727.57   628.8  727.43   638.4  729.34
     648  733.29   657.5  738.09   667.1   742.2   676.7  745.36   686.2  747.41
   754.5   751.9   774.2  752.54   823.3  753.17   862.6  754.76  1010.1  765.01
#Mann= 3 , 0 , 0
       0     .05       0   600.2    .045       0   638.4     .05       0
Bank Sta=600.2,638.4
XS Rating Curve= 0 ,0
Exp/Cntr=0.3,0.1

Type RM Length L Ch R = 1 ,9274.9  ,147,144.3,141.4
XS GIS Cut Line= 4
      1870898.37      649082.837     1871285.018      649038.344
     1871376.886      648861.878     1871518.655      648411.651
#Sta/Elev= 30
       0  802.32    87.6  781.96   126.5  771.62   184.9  757.64   204.3  753.43
   223.8  749.74   243.2  747.15     253  746.39   311.4   743.5   340.6  742.99
   389.2  743.88   408.2  743.46   427.1  741.34   455.5  733.77   474.5  730.17
   493.3  727.09   502.9  726.81   512.4  727.61   521.8  730.38   531.3  733.14
   540.8  735.04   559.7  737.64   578.7  739.56   647.2  741.84   696.3  742.28
   735.6  743.89     775   744.8   814.3  747.65   922.5  754.28  1060.2  765.46
#Mann= 3 , 0 , 0
       0     .05       0   474.5    .045       0   521.8     .06       0
Bank Sta=474.5,521.8
XS Rating Curve= 0 ,0
Exp/Cntr=0.3,0.1

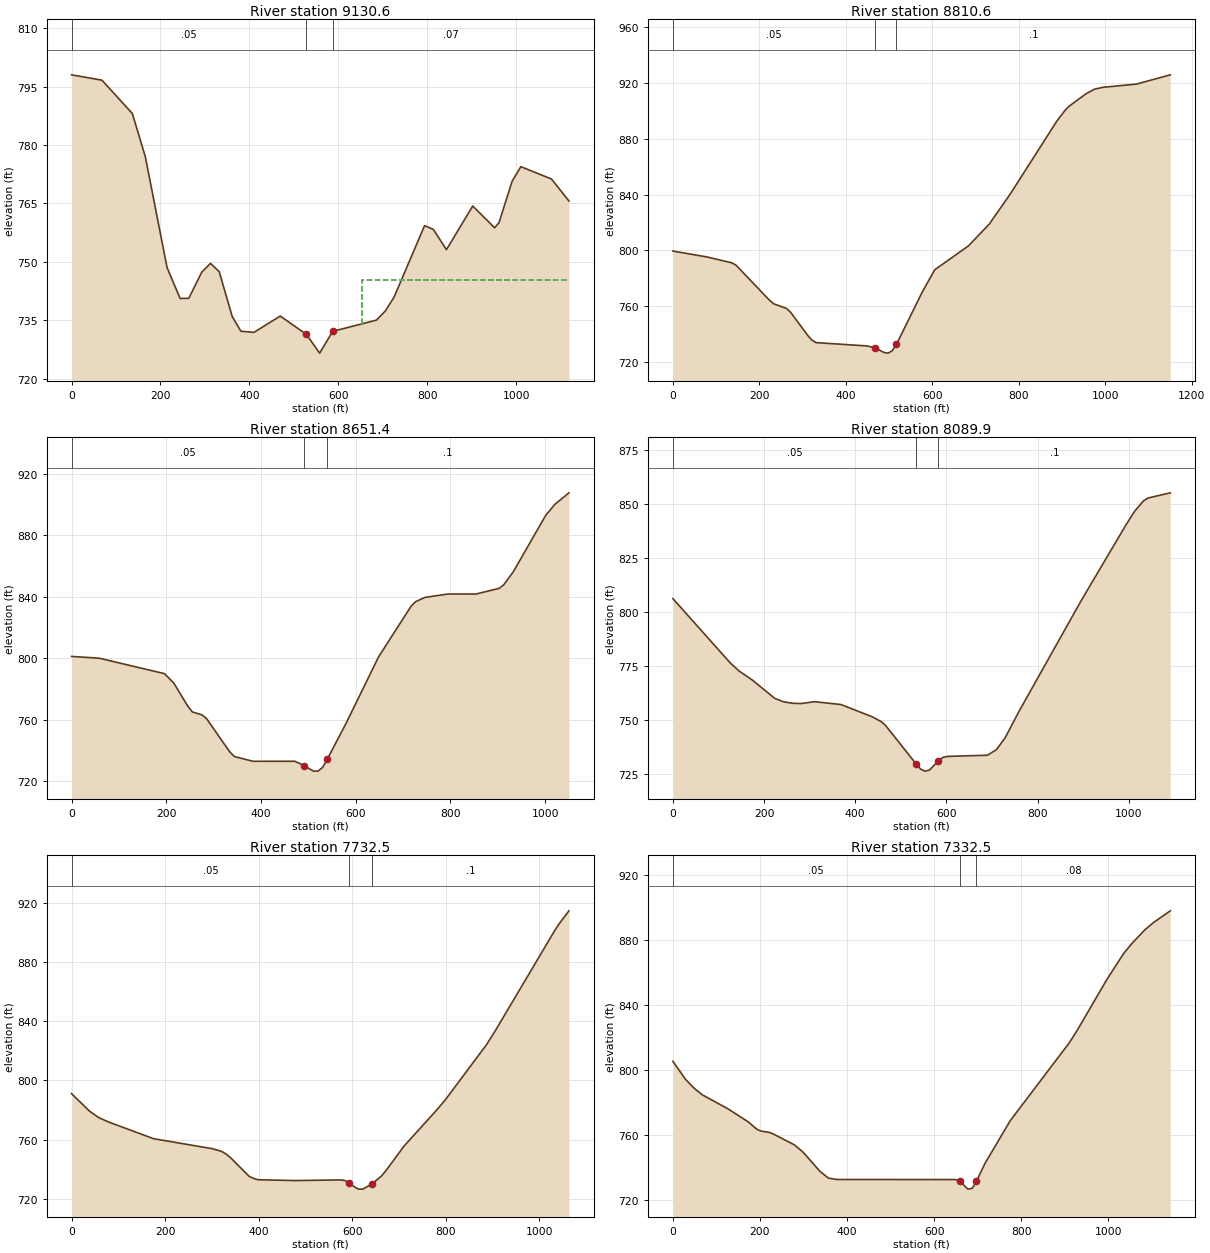
Type RM Length L Ch R = 1 ,9130.6  ,291.7,320,348.3
XS GIS Cut Line= 3
     1870978.036      649261.117     1871363.143      649195.462
     1871651.771      648527.059
#Sta/Elev= 30
       0     798    68.4  796.63   136.7  788.07     166  776.95   214.9  748.49
   244.2  740.58   263.7  740.62     293  747.36   312.5  749.58   332.1  747.47
   361.4  735.94   380.9  732.17   410.3  731.87   469.4  736.06   528.4  731.34
   557.9  726.54   587.4  732.13   685.8  735.02   705.5  737.33   725.2  740.86
     794  759.27   813.7  758.32   843.2   753.1   902.3  764.31   951.5  758.74
   961.3     760   990.8  770.65  1010.5  774.42  1079.4  771.25  1118.7  765.61
#Mann= 3 , 0 , 0
       0     .05       0   528.4    .045       0   587.4     .07       0
#XS Ineff= 2 , 0
          315.05  749.22  652.17          745.29
Permanent Ineff=
       F       F
Bank Sta=528.4,587.4
XS Rating Curve= 0 ,0
Exp/Cntr=0.3,0.1

Type RM Length L Ch R = 1 ,8810.6  ,154.9,159.2,163.4
XS GIS Cut Line= 4
     1870987.709      649349.542     1871367.483      649356.052
     1871593.178      649360.392     1871985.973      648982.788
#Sta/Elev= 30
       0  799.51    77.9  795.36   136.4  791.08   146.1   789.4     224   764.1
   233.7  761.69     263  758.39   272.7   755.5   311.7  739.17   321.4  735.77
   331.1  733.92   448.5  731.57   468.2  730.18   487.8  726.91   497.6   726.4
   507.4  728.09   517.2  732.73   576.1  769.76   605.6  786.11   683.4  803.16
     732  818.91   780.7  840.56   887.7  892.45   907.2  900.37   916.9  903.38
   955.8  912.22   975.3  915.48   994.8   916.8  1072.6  919.13  1150.4  925.75
#Mann= 3 , 0 , 0
       0     .05       0   468.2    .045       0   517.2      .1       0
Bank Sta=468.2,517.2
XS Rating Curve= 0 ,0
Exp/Cntr=0.3,0.1

Type RM Length L Ch R = 1 ,8651.4  ,556.1,561.5,567.4
XS GIS Cut Line= 3
     1870949.769      649370.955     1871402.205      649503.622
     1871968.612      649622.979
#Sta/Elev= 30
       0   801.1    58.9  799.91   196.4  789.87   216.1  783.67   245.6  768.65
   255.4  764.91     275  763.11   284.9   760.7     334     739   343.8  735.94
   383.1  732.82   471.5  732.85   491.1  730.04   510.7  726.42   520.5  726.44
   530.4  728.93   540.2  734.32   579.4  757.35   648.1  800.67   716.8  833.72
   726.6  836.74   746.2  839.52   795.2  841.74   854.1  841.72   903.2  845.43
     913  847.87   932.6   856.1  1001.3  892.96  1020.9  900.19  1050.3   907.6
#Mann= 3 , 0 , 0
       0     .05       0   491.1    .045       0   540.2      .1       0
Bank Sta=491.1,540.2
XS Rating Curve= 0 ,0
Exp/Cntr=0.3,0.1

Type RM Length L Ch R = 1 ,8089.9  ,351.9,357.4,360.6
XS GIS Cut Line= 3
     1870620.955      649703.274     1871137.448       649950.67
     1871593.178      650198.066
#Sta/Elev= 30
       0  806.18   126.2  776.25   145.6  772.54   174.7  768.32   223.2  759.92
   242.7  758.29   262.1  757.61   281.5  757.46   310.6  758.34   368.8  757.01
   436.8  751.36   456.2  749.18   465.9   747.5   533.9  729.38   543.6  727.02
   553.3  726.11     563  726.61   582.5  730.89   592.2  732.45     602  732.94
   690.1  733.49   709.7  736.05   729.2  741.68   758.6  753.55   895.6  805.17
   993.4  840.17    1013  846.69  1032.5  851.55  1042.3  852.84  1091.2  855.26
#Mann= 3 , 0 , 0
       0     .05       0   533.9    .045       0   582.5      .1       0
Bank Sta=533.9,582.5
XS Rating Curve= 0 ,0
Exp/Cntr=0.3,0.1

Type RM Length L Ch R = 1 ,7732.5  ,390.9,400,410.7
XS GIS Cut Line= 3
     1870540.395       649893.22     1871013.945      650282.718
     1871381.996      650542.156
#Sta/Elev= 30
       0  791.04    38.9  779.11    58.4  774.85    77.9  772.06   175.2  760.64
   301.7  753.84   321.2     752   330.9  750.14   340.6  747.62   379.6  735.27
   389.3  733.75     399  732.92   476.9  732.36   574.2  732.79     584  732.44
   593.7  730.98   603.4  728.38   613.2  726.63   622.9  726.58   642.5  730.17
   662.1  735.29   671.9  738.92     711  755.68   779.6  779.62   799.2  786.89
   887.2  824.12   906.8  833.95  1034.1  901.75  1043.9  906.36  1063.4  914.47
#Mann= 3 , 0 , 0
       0     .05       0   593.7    .045       0   642.5      .1       0
Bank Sta=593.7,642.5
XS Rating Curve= 0 ,0
Exp/Cntr=0.3,0.1

Type RM Length L Ch R = 1 ,7332.5  ,492.8,502.2,511.3
XS GIS Cut Line= 4
      1870375.98      649903.964     1870482.721      650108.525
     1870693.912      650513.251     1870905.965      650915.406
#Sta/Elev= 30
       0  805.59    28.8   794.6    48.1  789.22    67.3  785.01     125  776.61
     173  768.35   192.3  763.92   201.9  762.71   221.1   761.9   230.7  760.88
   279.3  754.15   298.7  749.78   337.6  737.94     357  733.79   376.4  732.91
   648.4   732.9   658.1     732   677.5  726.99   687.2  727.48   696.9  731.72
   716.3  742.68   774.3  769.01   909.7  816.83   929.1     825   996.8  856.11
  1035.5   872.1  1054.8  878.33  1083.8  886.47  1103.2  890.86  1141.9   898.1
#Mann= 3 , 0 , 0
       0     .05       0   658.1    .045       0   696.9     .08       0
Bank Sta=658.1,696.9
XS Rating Curve= 0 ,0
Exp/Cntr=0.3,0.1

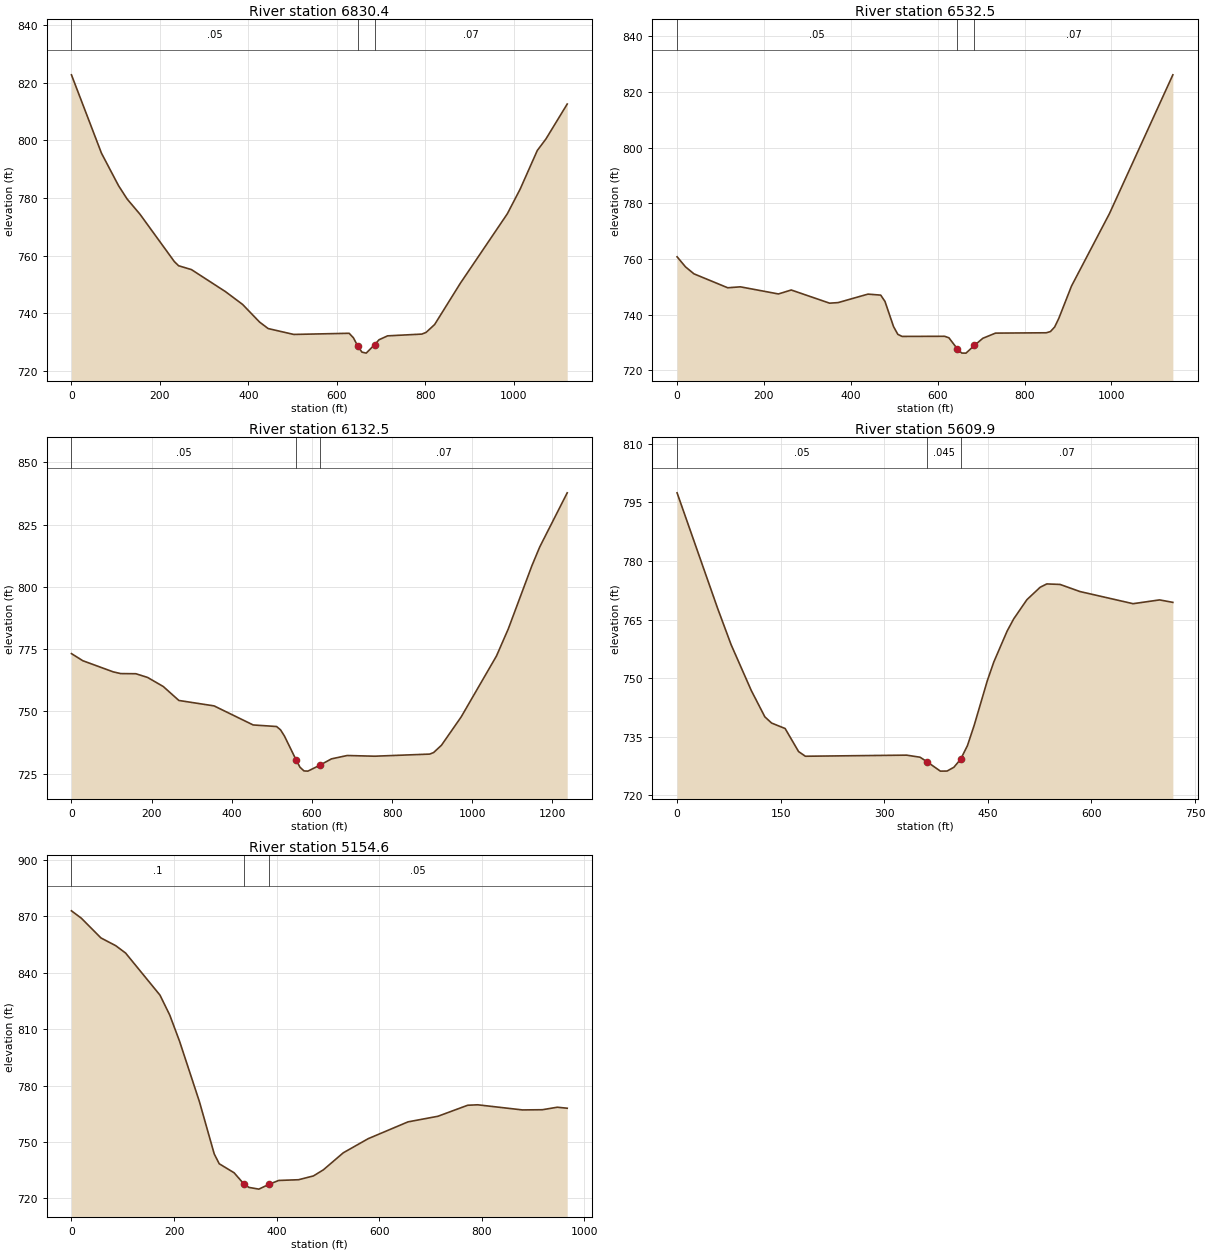
Type RM Length L Ch R = 1 ,6830.4  ,297.9,297.8,291
XS GIS Cut Line= 4
     1870165.816      649917.697     1870184.975      650168.769
     1870217.961      650601.061     1870256.578      651034.333
#Sta/Elev= 30
       0  822.76    67.8   795.6   106.5  784.29   125.9  779.68     155  774.39
   232.4  758.02   242.1  756.55   271.1  755.22   348.2  747.56   386.7  743.14
   425.2  737.01   444.5  734.77   502.3  732.73   627.5  733.13   637.2  731.56
   646.8  728.74   656.4   726.6   666.1  726.25   685.4  729.24     695  730.88
   714.4  732.24   791.7  732.85   801.4  733.44   820.7  736.17   878.7  750.46
     985  774.58    1014  783.15  1052.7  796.53    1072  800.47  1120.3  812.63
#Mann= 3 , 0 , 0
       0     .05       0   646.8    .045       0   685.4     .07       0
Bank Sta=646.8,685.4
XS Rating Curve= 0 ,0
Exp/Cntr=0.3,0.1

Type RM Length L Ch R = 1 ,6532.5  ,406,400,388.7
XS GIS Cut Line= 4
      1869869.87      649937.036     1869885.985      650150.111
     1869920.029      650600.244     1870095.045      651043.102
#Sta/Elev= 30
       0  760.83    19.4  757.21    38.8  754.71   116.6   749.7   145.7  750.04
   233.3  747.48   262.8   748.9   351.1  744.17   370.7  744.37   439.4  747.42
   468.8  747.06   478.6  744.78   498.3  735.75   508.1  732.98   517.9  732.22
     616  732.27   625.8  731.72   645.5   727.7   655.3  726.24   665.1  726.22
   684.5  729.02     704  731.56   733.1  733.41   849.8  733.53   859.5  733.97
   869.2  735.61   878.9  738.76     908  750.33   995.5   776.4  1141.3  826.21
#Mann= 3 , 0 , 0
       0     .05       0   645.5    .045       0   684.5     .07       0
Bank Sta=645.5,684.5
XS Rating Curve= 0 ,0
Exp/Cntr=0.3,0.1

Type RM Length L Ch R = 1 ,6132.5  ,513,522.6,541.5
XS GIS Cut Line= 4
     1869325.357      650072.767     1869380.268      650223.796
     1869523.569      650617.938     1870000.609      651069.437
#Sta/Elev= 30
       0  773.18    28.4  770.32     104  765.86   122.9  765.16   160.7   765.1
     190  763.61     229  759.98     268  754.37   355.8  752.19   453.3  744.54
   511.8  743.91   521.6  742.58   531.3  740.12   560.6  730.48   570.3  727.54
   580.1  726.09   589.9     726   619.3  728.35   648.7  730.92   687.9  732.27
   756.6  731.99   893.8  732.84   903.6  733.47   923.2   736.4   972.2  747.73
  1060.4  772.23  1089.9  783.11  1148.7  808.44  1168.3     816  1236.9  837.73
#Mann= 3 , 0 , 0
       0     .05       0   560.6    .045       0   619.3     .07       0
Bank Sta=560.6,619.3
XS Rating Curve= 0 ,0
Exp/Cntr=0.3,0.1

Type RM Length L Ch R = 1 ,5609.9  ,481.5,455.4,430.2
XS GIS Cut Line= 4
     1869044.784      650233.005     1869027.422      650662.693
     1869030.895      650739.082     1869148.082      650914.863
#Sta/Elev= 30
       0  797.45    58.6  767.92    78.2  758.58   107.5  746.82   127.1   740.1
   136.8  738.52   156.4  737.12   175.9  731.22   185.7  730.02   332.3   730.3
   351.8  729.77   361.6  728.64   381.2  726.21   390.9  726.23   400.7  727.19
   410.5  729.24   420.3   732.7     430  737.85   449.2  749.38   458.7  754.21
   477.8  762.04   487.4  765.19   506.5   770.1   525.7  773.28   535.3  774.13
   554.5     774   583.3  772.18   660.2  769.07   698.6  770.04   717.8  769.41
#Mann= 3 , 0 , 0
       0     .05       0   361.6    .045       0   410.5     .07       0
Bank Sta=361.6,410.5
XS Rating Curve= 0 ,0
Exp/Cntr=0.3,0.1

Type RM Length L Ch R = 1 ,5154.6  ,232.9,222,218.5
XS GIS Cut Line= 4
     1868303.898      650437.432     1868512.231      650535.089
     1868735.756      650650.106     1869135.061      650925.714
#Sta/Elev= 30
       0  872.79    19.2  868.89    57.5  858.39    86.3  854.28   105.5  850.39
   172.6  828.02   191.7   817.4   210.9  803.42   249.4  771.51   278.4  743.65
   288.1  738.45   317.1  733.66   336.4  727.65   346.1  725.88   365.4  724.97
   384.8  727.48   404.1  729.58   442.8  729.96   471.8  731.98   491.2  735.23
     530  744.27   578.5  751.76   656.1  760.69   714.4  763.66   772.6  769.52
     792  769.76   879.3  767.04   918.1  767.14   947.2  768.47   966.6  767.94
#Mann= 3 , 0 , 0
       0      .1       0   336.4    .045       0   384.8     .05       0
Bank Sta=336.4,384.8
XS Rating Curve= 0 ,0
Exp/Cntr=0.3,0.1