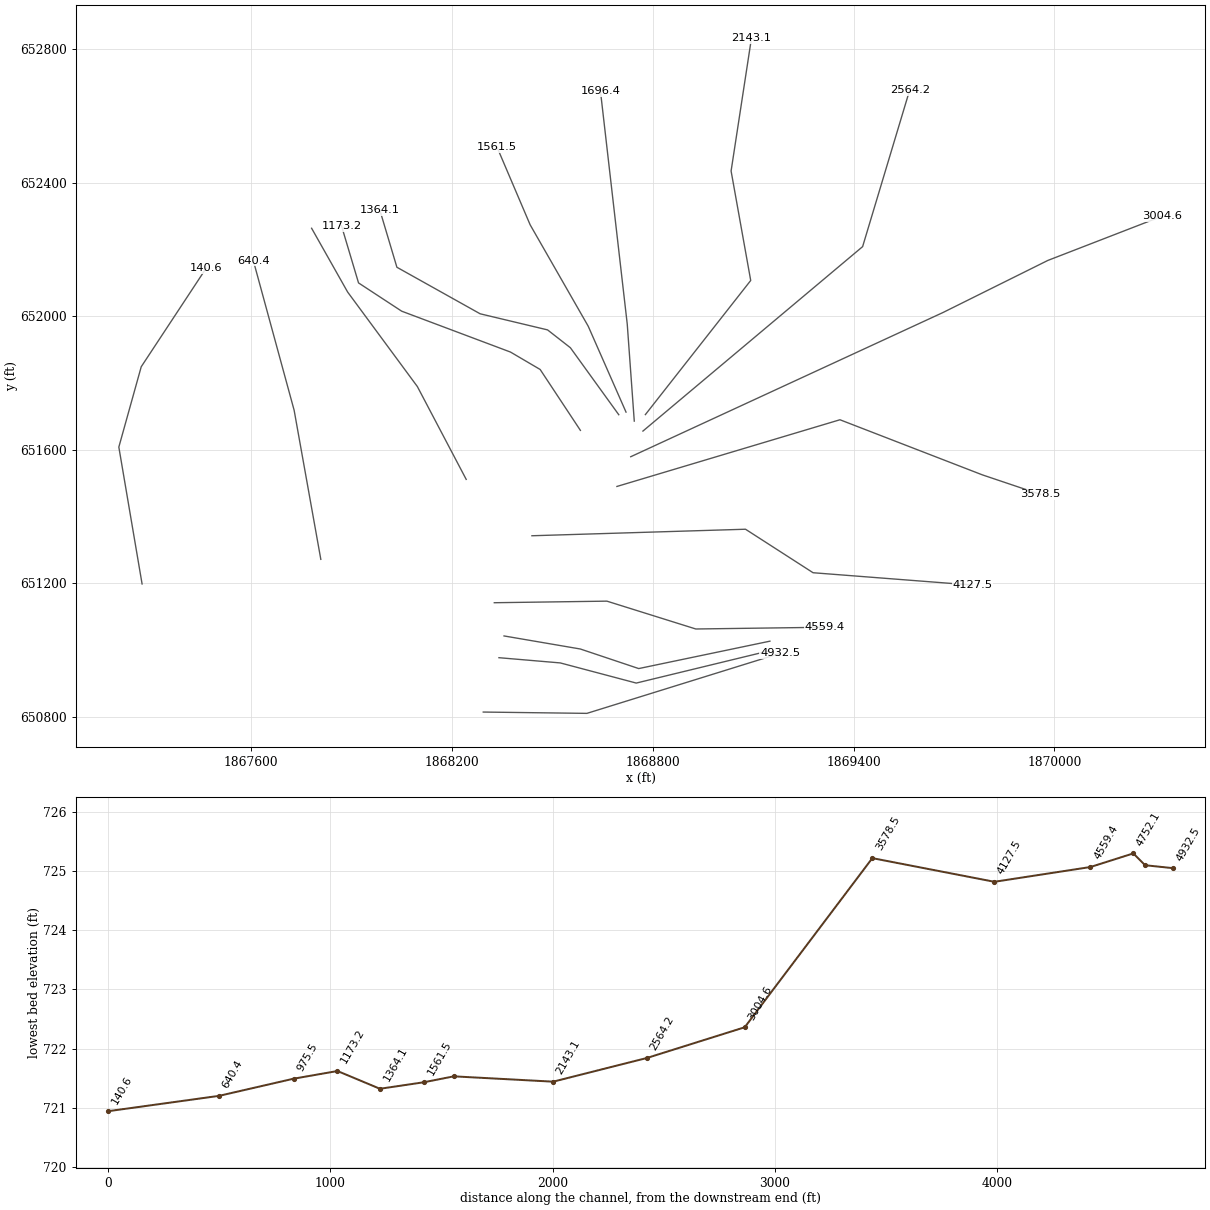
HEC-RAS study LFSpringCk.prj: LFSpringCk

--- LFSpringCk.g01 (geometry) --- (continued)

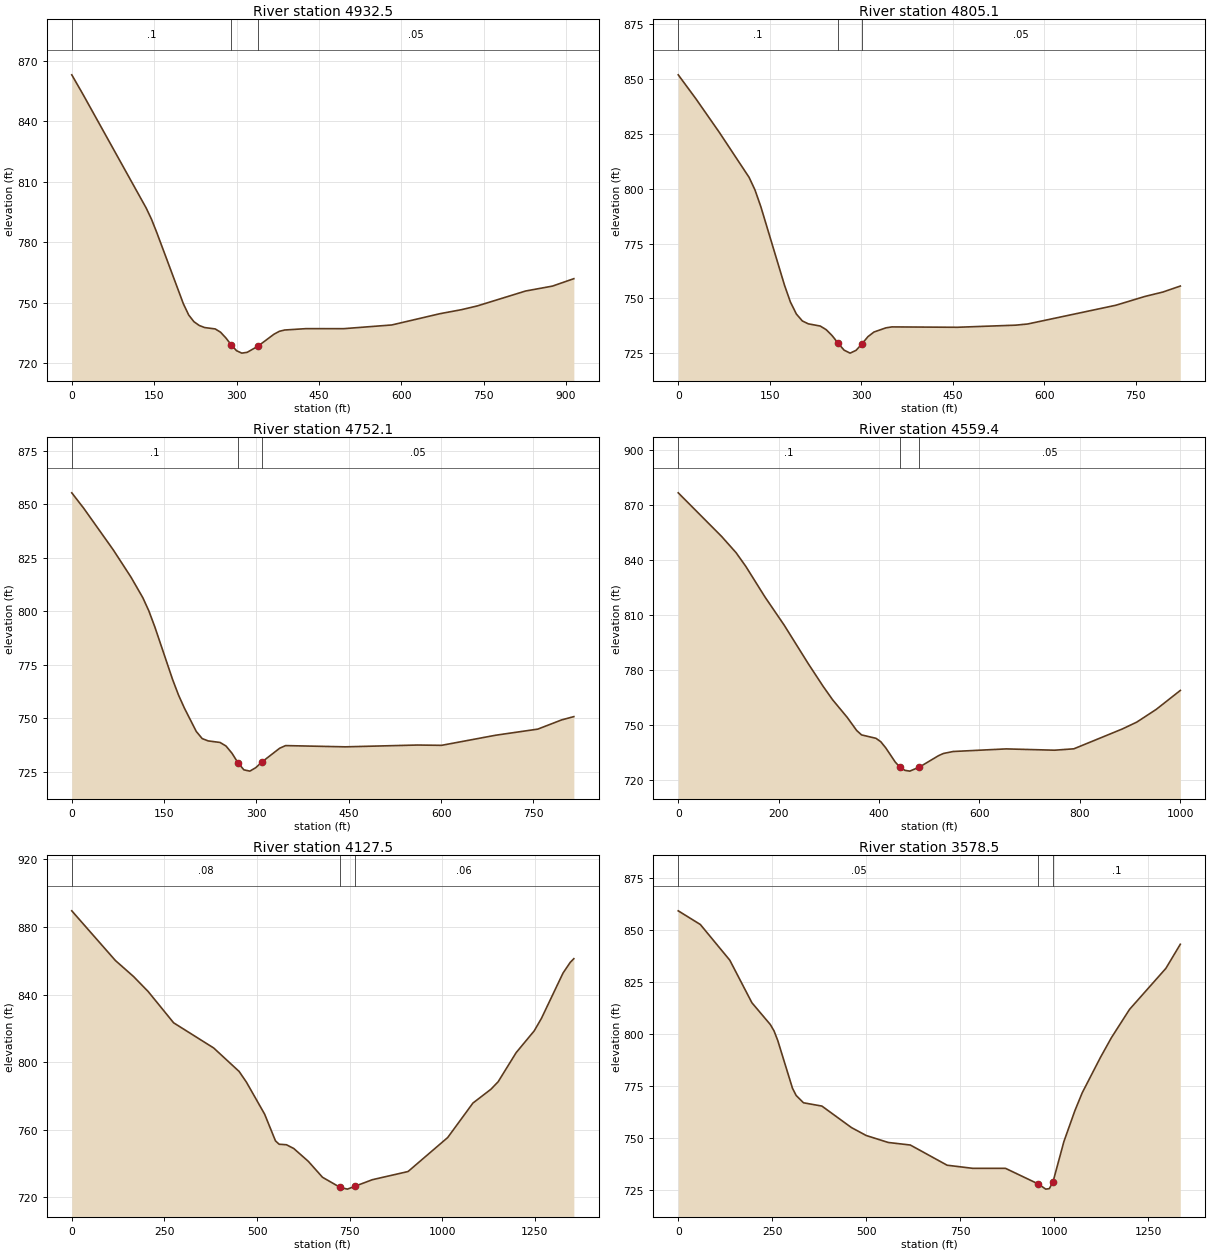
Type RM Length L Ch R = 1 ,4932.5  ,133,127.5,114.6
XS GIS Cut Line= 3
     1868293.905      650815.083     1868603.505      650811.129
     1869180.634      650990.818
#Sta/Elev= 30
       0  863.13    19.4  853.94   135.5  797.04   145.1  791.52   154.8  784.86
   203.2  749.53   212.9  743.96   222.5  740.62   232.2  738.76   241.9  737.74
   261.2  737.05   270.9  735.43   280.6  732.58   290.3  729.16     300  726.25
   309.6  725.05   319.4  725.45   338.9  728.48   368.1  734.43   377.9  735.87
   387.6  736.52   426.6   737.2   494.9  737.18   582.6  739.02   670.4  744.62
   709.4   746.6   738.6  748.49   826.3  755.87   875.1   758.3   914.1  761.99
#Mann= 3 , 0 , 0
       0      .1       0   290.3    .045       0   338.9     .05       0
Bank Sta=290.3,338.9
XS Rating Curve= 0 ,0
Exp/Cntr=0.3,0.1

Type RM Length L Ch R = 1 ,4805.1  ,54.4,52.9,51.5
XS GIS Cut Line= 4
     1868340.791      650977.797      1868523.95      650962.172
     1868750.947      650901.842     1869143.742      650997.328
#Sta/Elev= 30
       0  851.94      29  841.01    67.7  825.57   116.1  805.23   125.8  799.47
   135.4  791.83   174.2  756.04   183.8  748.44   193.6  742.94   203.4  739.77
   213.2  738.45   232.8  737.44   242.5  735.79   252.3  733.06   262.1   729.6
   271.8  726.47   281.7   725.1   291.5  726.37   301.3  729.38     311  732.63
   320.8  734.72   340.4  736.62   350.2  737.05   457.2  736.88   553.4  737.85
   572.7  738.38   717.1  746.91   765.2  750.96   794.1  752.92   822.9  755.67
#Mann= 3 , 0 , 0
       0      .1       0   262.1    .045       0   301.3     .05       0
Bank Sta=262.1,301.3
XS Rating Curve= 0 ,0
Exp/Cntr=0.3,0.1

Type RM Length L Ch R = 1 ,4752.1  ,189.7,192.7,197
XS GIS Cut Line= 4
     1868355.981      651042.901     1868583.846      651003.839
     1868758.325      650945.245     1869150.252      651027.276
#Sta/Elev= 30
       0  855.45    19.3  848.28    67.4  828.78    96.3  815.98   115.6  806.32
   125.2  800.26   134.9  792.79   163.8  768.16   173.4   760.9     183  754.77
   202.3  743.84   211.9  740.52   221.6  739.43   240.9  738.71   250.6  737.04
   260.2   733.7   269.9  729.26   279.6  725.91   289.3   725.3     299  726.93
   308.7  729.53   337.8  736.01   347.4  737.24   444.5  736.66   561.7   737.5
   600.8  737.36   688.7  742.09   757.1  744.94   796.1  749.28   815.7  750.79
#Mann= 3 , 0 , 0
       0      .1       0   269.9    .045       0   308.7     .05       0
Bank Sta=269.9,308.7
XS Rating Curve= 0 ,0
Exp/Cntr=0.3,0.1

Type RM Length L Ch R = 1 ,4559.4  ,439.9,432,424.2
XS GIS Cut Line= 4
     1868326.923      651142.346     1868663.273      651147.068
     1868928.898      651063.734     1869314.315      651068.943
#Sta/Elev= 30
       0   876.7    86.5  852.91   115.3  844.06   134.6  836.63     173  819.87
   211.4  804.47   259.5  783.42   288.3  771.42   307.6  763.92   336.4  754.44
   355.6  747.17   365.2  744.81     394  742.94   403.6  741.06   413.2  737.82
   432.4  729.99     442  727.08   451.6   725.5   461.2  725.07   480.4  727.27
   518.8  733.53   528.4  734.69   547.6  735.76   653.3  737.18   749.7  736.47
   788.2  737.23   884.6  748.03   913.5  751.78     952  758.66  1000.2  769.03
#Mann= 3 , 0 , 0
       0      .1       0     442    .045       0   480.4     .05       0
Bank Sta=442,480.4
XS Rating Curve= 0 ,0
Exp/Cntr=0.3,0.1

Type RM Length L Ch R = 1 ,4127.5  ,544.9,549,551.6
XS GIS Cut Line= 4
     1868439.315      651342.814     1869077.336      651362.346
     1869279.159      651232.137     1869754.419      651195.245
#Sta/Elev= 30
       0  889.56   117.8  860.14     167  850.62   206.2  841.79     275  823.26
     383  808.38   451.7  794.48   471.4  788.16   520.5  769.24   549.9  753.37
   559.8  751.39   579.4  751.09     599   748.9   638.3  741.31   676.8  731.83
   724.8   725.8     744  724.82   763.2  726.42   811.2  730.39   907.7  735.24
  1014.7  755.36  1082.8  775.76  1131.4  783.94  1150.9  788.38  1199.5  805.62
  1248.2   818.5  1267.6  825.84    1326  852.72  1345.5  859.06  1355.2  861.23
#Mann= 3 , 0 , 0
       0     .08       0   724.8    .045       0   763.2     .06       0
Bank Sta=724.8,763.2
XS Rating Curve= 0 ,0
Exp/Cntr=0.3,0.1

Type RM Length L Ch R = 1 ,3578.5  ,571.3,573.9,609.2
XS GIS Cut Line= 4
     1868693.221      651490.384     1869359.454      651690.037
     1869784.801      651525.106     1869958.412      651466.512
#Sta/Elev= 30
       0  859.06    58.8  852.48   137.1  835.32   195.9  814.85   244.9  804.36
   254.7  801.32   264.5  796.76   303.7  773.76   313.5  770.27   333.1  766.74
     382  765.16   460.4  754.84   499.6  751.02   558.4  747.66   617.1  746.43
   714.9  736.72   782.9  735.22   870.2  735.21   957.6  727.67     977  725.22
   986.7  725.46   996.4  728.71  1025.5  748.16  1054.6  762.95  1074.1  771.55
  1122.6  788.58  1151.7  798.05  1199.9  811.66  1296.4  831.36  1334.9  842.98
#Mann= 3 , 0 , 0
       0     .05       0   957.6    .045       0   996.4      .1       0
Bank Sta=957.6,996.4
XS Rating Curve= 0 ,0
Exp/Cntr=0.3,0.1

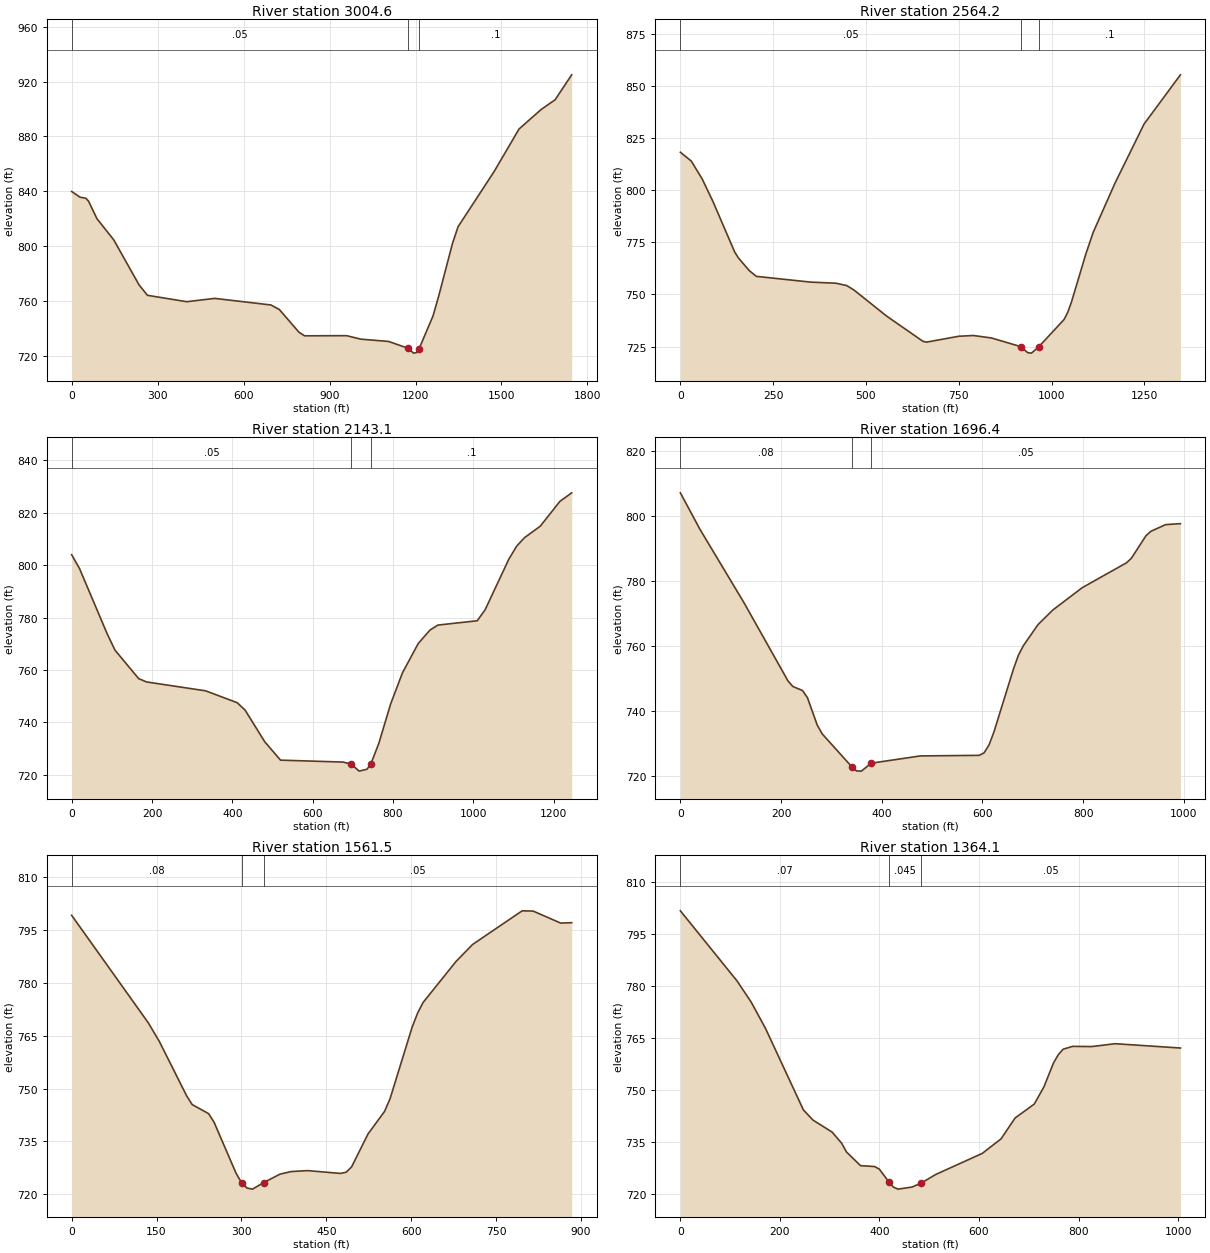
Type RM Length L Ch R = 1 ,3004.6  ,421.7,440.4,459
XS GIS Cut Line= 4
     1868734.454      651579.359     1869667.613      652011.217
     1869980.386       652166.92     1870322.995      652299.846
#Sta/Elev= 30
       0  839.94    29.4  835.81      49   835.1    58.8  832.99    88.1  820.23
   146.9  804.76     235  772.08   264.4  764.44   401.5  759.78   499.4  762.19
   695.3  757.41   724.7   754.1   793.2  737.59   812.8  734.95   959.7  735.06
  1008.7  732.54  1105.9  730.86  1173.8  725.93  1193.2  722.36  1202.8  722.67
  1212.6  725.58  1261.2  749.46  1280.6   763.6  1329.1  802.21  1348.5  814.31
  1474.3  854.46  1561.4  885.45  1638.7  899.68  1687.1  906.69  1745.1  924.86
#Mann= 3 , 0 , 0
       0     .05       0  1173.8    .045       0  1212.6      .1       0
Bank Sta=1173.8,1212.6
XS Rating Curve= 0 ,0
Exp/Cntr=0.3,0.1

Type RM Length L Ch R = 1 ,2564.2  ,409.9,421.1,431.6
XS GIS Cut Line= 3
     1868770.912      651656.182     1869427.162      652208.266
     1869567.787      652677.016
#Sta/Elev= 30
       0  818.27    29.2  814.06    58.5  805.53    87.7  794.65   146.2  770.41
   155.9  767.64   185.2  761.51   204.6  758.69   350.8  755.93     419   755.4
   448.3  754.26   467.8   752.1   555.5  739.64   652.9  727.57   662.7  727.11
   750.4  729.95   789.4  730.29   838.1  729.11   916.3     725   935.9  722.04
   945.7  721.84   965.3  724.84  1033.8  738.03  1043.6  741.48  1053.4  746.29
  1092.5  769.56  1112.1  779.83  1170.8  803.44  1249.1  831.81    1347  855.43
#Mann= 3 , 0 , 0
       0     .05       0   916.3    .045       0   965.3      .1       0
Bank Sta=916.3,965.3
XS Rating Curve= 0 ,0
Exp/Cntr=0.3,0.1

Type RM Length L Ch R = 1 ,2143.1  ,448.4,446.7,445
XS GIS Cut Line= 4
     1868778.204      651705.488     1869092.874      652106.964
      1869034.28      652434.655     1869095.044       652831.79
#Sta/Elev= 30
       0  803.98    19.6   798.7    88.3  773.86   107.9  767.58   166.8  756.73
   186.4  755.46   333.5  752.07     412  747.54   431.6  744.74   480.7  732.62
   519.9  725.63   676.5  724.89   696.1  724.04   715.7  721.44   735.3  722.17
   745.1   724.3   764.7  732.09     794  747.05   823.4  758.92   862.6   770.1
     892  775.26   911.6  777.15  1009.6   778.8  1029.2  782.99    1088  802.21
  1107.6  807.24  1127.2  810.49  1166.4  814.87  1215.4  824.35  1244.7   827.6
#Mann= 3 , 0 , 0
       0     .05       0   696.1    .045       0   745.1      .1       0
Bank Sta=696.1,745.1
XS Rating Curve= 0 ,0
Exp/Cntr=0.3,0.1

Type RM Length L Ch R = 1 ,1696.4  ,125.2,134.8,144.6
XS GIS Cut Line= 3
     1868745.044      651686.044     1868724.037      651976.495
     1868644.002      652673.891
#Sta/Elev= 30
       0  807.24    38.8  796.03   126.2  773.44   213.6  749.35   223.3  747.61
   242.7  746.34   252.4  744.14   271.8  735.73   281.5  733.04     340  722.95
   349.7   721.6   359.5  721.53     379  723.97   476.4  726.21   593.4  726.39
   603.2  727.15     613  729.57   622.7  733.55   661.7  753.03   671.4  757.21
   681.2  760.14   710.4  766.66   739.7  771.14   798.2  778.03   885.9  785.67
   895.7  787.06   924.9  794.05   934.7  795.41   963.9  797.45   993.2  797.75
#Mann= 3 , 0 , 0
       0     .08       0     340    .045       0     379     .05       0
Bank Sta=340,379
XS Rating Curve= 0 ,0
Exp/Cntr=0.3,0.1

Type RM Length L Ch R = 1 ,1561.5  ,151.8,197.5,241.4
XS GIS Cut Line= 4
     1868720.391      651712.953     1868607.544      651969.898
     1868433.933      652273.717     1868334.975      652506.356
#Sta/Elev= 30
       0  799.23   135.5  768.66   154.8  763.42   203.2  747.92   212.9  745.46
   241.9  742.89   251.6  740.44   290.4  725.96   300.1  723.28   309.8  721.74
   319.5  721.43     339  723.27   368.1  725.69   387.6  726.42   416.7  726.69
     475  725.89   484.8  726.23   494.5  727.73   523.6  737.11   552.8  743.52
   562.5  747.12   601.4   767.4   611.1  771.42   620.8  774.46   679.2  786.15
   708.4  790.96   795.9  800.51   815.3  800.44   863.9  797.03   883.4  797.14
#Mann= 3 , 0 , 0
       0     .08       0   300.1    .045       0     339     .05       0
Bank Sta=300.1,339
XS Rating Curve= 0 ,0
Exp/Cntr=0.3,0.1

Type RM Length L Ch R = 1 ,1364.1  ,202.8,190.9,175.9
XS GIS Cut Line= 6
      1868698.69      651705.141     1868554.159      651905.662
     1868486.016      651959.047     1868284.627      652007.224
     1868035.929      652146.547     1867985.148       652317.12
#Sta/Elev= 30
       0  801.77   114.1  781.46   142.6  775.31   171.1  767.76   247.2  744.22
   266.4  741.28   304.9  737.81   324.1  734.58   333.7  732.07     362   728.1
   390.2  727.85   399.6  727.13   418.5   723.5   427.9  721.92   437.3  721.32
   465.5  721.92   484.3   723.1   512.6  725.52   606.7  731.66   644.3  735.84
   672.5  741.88     711   745.9   730.3  750.84   749.6  757.75   759.2  760.15
   768.9  761.76   788.2  762.59   826.7  762.53   873.5  763.36  1004.7  762.11
#Mann= 3 , 0 , 0
       0     .07       0   418.5    .045       0   484.3     .05       0
Bank Sta=418.5,484.3
XS Rating Curve= 0 ,0
Exp/Cntr=0.3,0.1

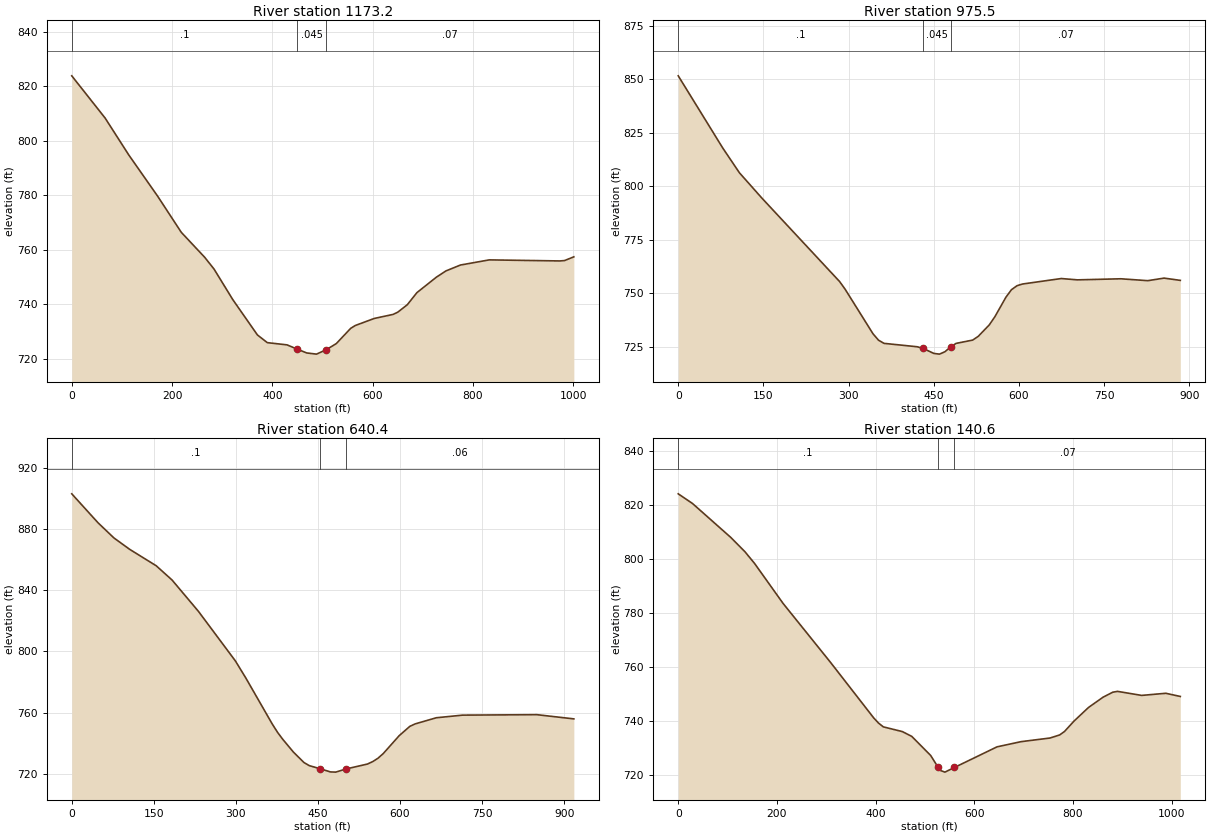
Type RM Length L Ch R = 1 ,1173.2  ,228.5,197.6,171.6
XS GIS Cut Line= 6
     1868584.106      651658.266     1868463.881      651840.557
     1868375.339      651892.641     1868050.252      652015.037
     1867921.346      652099.672     1867870.565      652270.245
#Sta/Elev= 30
       0  823.85    66.5  808.34   113.9  794.72   170.9  779.73   218.4  766.36
   265.1  757.18   283.7  752.86   321.1  741.64   370.2  728.66   389.9  725.84
   429.2  725.02   448.8  723.51   468.5  722.05   488.1  721.62   507.8  723.29
   527.4  725.48   556.1  731.08   565.5  732.15   603.1  734.72   640.7  736.21
   650.1  737.04     669  739.76   688.2  744.21   726.8  749.86     746  752.18
     775  754.35   832.5  756.24     973  755.85   982.4  755.98  1001.1  757.36
#Mann= 3 , 0 , 0
       0      .1       0   448.8    .045       0   507.8     .07       0
Bank Sta=448.8,507.8
XS Rating Curve= 0 ,0
Exp/Cntr=0.3,0.1

Type RM Length L Ch R = 1 ,975.5   ,343.9,335.1,326.2
XS GIS Cut Line= 4
     1868242.961      651511.564     1868097.127      651789.342
     1867888.794      652072.328     1867781.155        652263.3
#Sta/Elev= 30
       0  851.71    78.4  817.94   107.8  806.34   147.1  794.57   284.3  755.44
   294.1  751.81     343  731.04   352.8  728.01   362.5  726.53   421.1  724.93
   430.9   724.2   450.4  721.81   460.2  721.49   469.9  722.63   479.7  724.85
   489.4  726.51   518.7  728.06   528.5  729.82     548   735.2   557.8     739
   577.3  748.16     587  751.64   596.8  753.51   606.6   754.3   674.7  756.86
   703.3  756.24   779.5  756.74   827.2  755.86   855.8  757.06   884.4     756
#Mann= 3 , 0 , 0
       0      .1       0   430.9    .045       0   479.7     .07       0
Bank Sta=430.9,479.7
XS Rating Curve= 0 ,0
Exp/Cntr=0.3,0.1

Type RM Length L Ch R = 1 ,640.4   ,511.9,499.8,487.7
XS GIS Cut Line= 3
     1867808.671        651272.2     1867728.955      651718.483
     1867607.014      652166.556
#Sta/Elev= 30
       0  902.84    48.2  883.87    77.2  874.01   106.1  866.55   154.3   855.9
   183.3  846.59   231.5  826.15     299  793.82   318.3  782.54   366.5  752.58
   376.2  747.14   385.8  742.56   405.1  734.29   424.4  727.47   434.1  725.44
   453.4  723.47   472.7  721.34   482.4   721.2   501.7   723.3   540.4  726.47
   550.1  728.07   559.8  730.29   569.4  733.33   598.5     745   617.8  751.05
   627.5  752.66   666.2  756.68   714.6   758.4     850   758.7   917.7  755.95
#Mann= 3 , 0 , 0
       0      .1       0   453.4    .045       0   501.7     .06       0
Bank Sta=453.4,501.7
XS Rating Curve= 0 ,0
Exp/Cntr=0.3,0.1

Type RM Length L Ch R = 1 ,140.6   ,146,140.6,135.2
XS GIS Cut Line= 4
     1867274.731      651198.544     1867205.287      651608.266
     1867272.187      651848.729     1867465.704      652142.988
#Sta/Elev= 30
       0  824.22      29  820.62   106.3  808.07   135.3  802.71   154.6   798.4
   212.6  783.52   309.3  761.51   396.2  741.04   405.9  739.14   415.6  737.74
     454  735.99   473.2  734.21   511.6  727.11   526.2  722.83   530.8  721.58
   540.4  720.94   559.6  722.66     646  730.32   694.5  732.24   753.2  733.59
   772.8  734.73   782.6     736   802.1   739.9   831.5  744.95   860.8  748.74
   880.4  750.59   890.2  750.91   939.1  749.41     988   750.2  1017.4  749.02
#Mann= 3 , 0 , 0
       0      .1       0   526.2    .045       0   559.6     .07       0
Bank Sta=526.2,559.6
XS Rating Curve= 0 ,0
Exp/Cntr=0.3,0.1

Chan Stop Cuts=-1
Use User Specified Reach Order=0
Composite Channel Slope=5